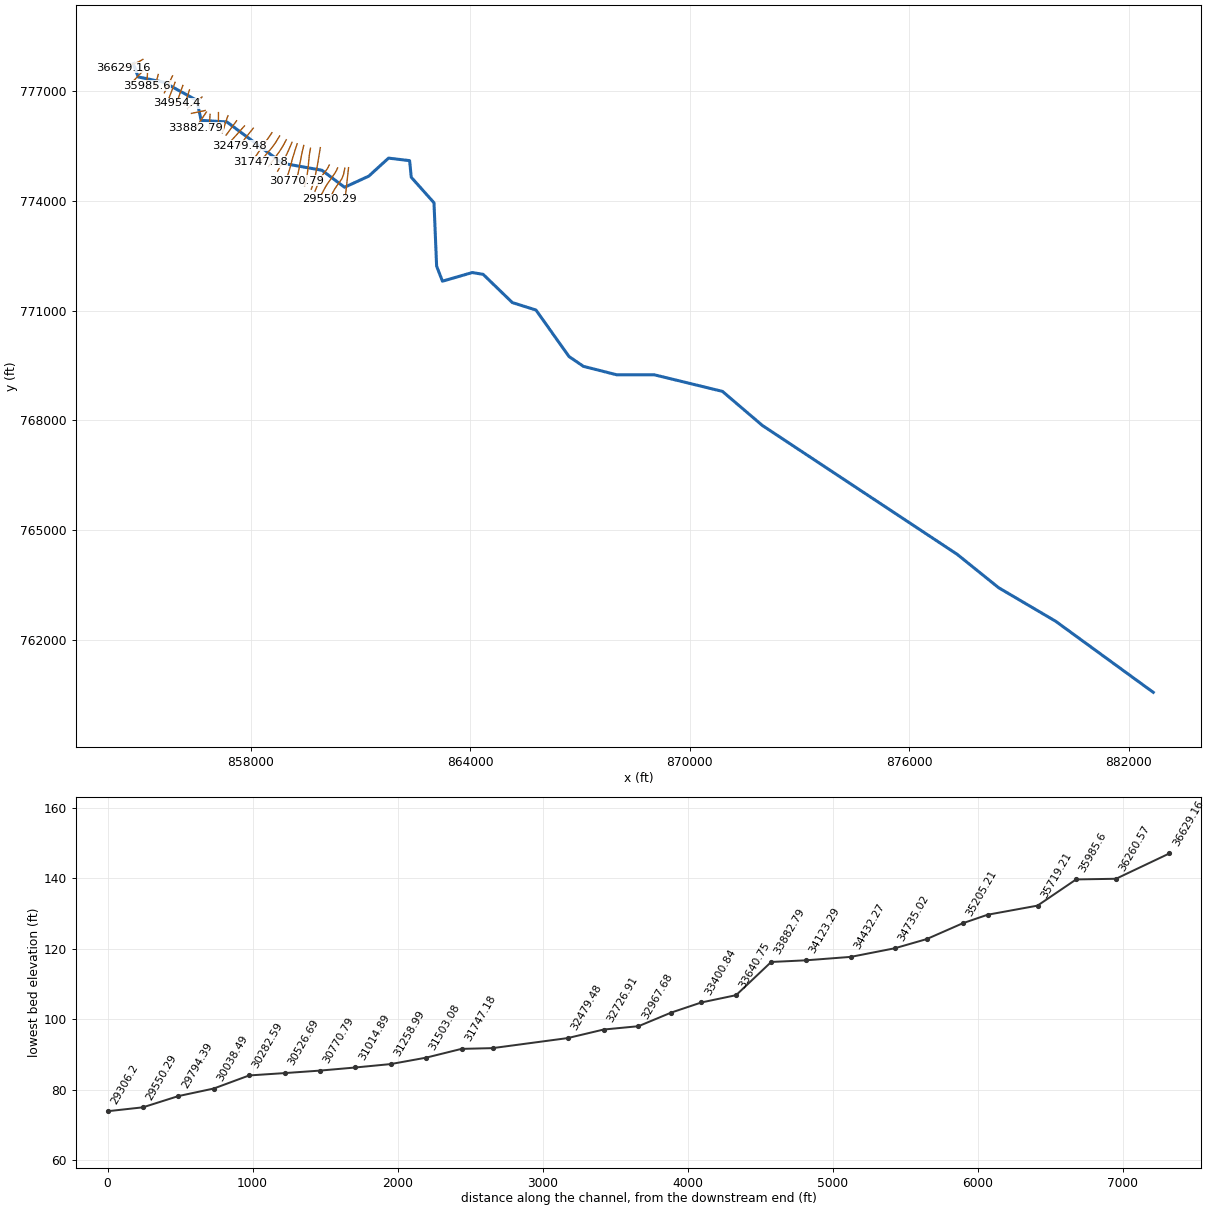
--- 9741_ras.prj (project) ---

Proj Title=9741
Current Plan=p01
Default Exp/Contr=0.3,0.1
English Units
Geom File=g01
Flow File=f01
Plan File=p01
Y Axis Title=Elevation
X Axis Title(PF)=Main Channel Distance
X Axis Title(XS)=Station
BEGIN DESCRIPTION:
RFD model 9741 exported to HEC-RAS
END DESCRIPTION:

--- 9741_ras.p01 (plan) ---

Plan Title=Plan 01
Program Version=4.10
Short Identifier=Plan 01
Geom File=g01
Flow File=f01
Subcritical Flow
Calc Critical at every XS
Secant Critical Depth

--- 9741_ras.f01 (steady flow) ---

Flow Title=Flow 01
Program Version=5.01
Number of Profiles= 6
Profile Names=10yr,25yr,50yr,100yr,100plus,500yr
River Rch & RM=9741,69,36629.16
 7787.48 13364.915750.2120566.7925360.6836718.66
River Rch & RM=9741,69,36260.57
 7830.37 13439.915837.6320677.9525497.7436901.42
River Rch & RM=9741,69, 35985.6
 7834.7313447.5315846.5220689.2525511.6836919.99
River Rch & RM=9741,69,35719.21
 7841.64 13459.6 15860.620707.1425533.7436949.41
River Rch & RM=9741,69,35375.03
 8033.0913794.4416250.8321203.0926145.2937763.83
River Rch & RM=9741,69,35205.21
 8040.3513807.1416265.64 21221.926168.4837794.69
River Rch & RM=9741,69, 34954.4
 8065.77 13851.616317.4521287.7126249.6437902.65
River Rch & RM=9741,69,34735.02
 8074.8413867.4816335.9521311.2226278.62 37941.2
River Rch & RM=9741,69,34432.27
 8856.0615235.4217929.1123332.5128771.0541244.09
River Rch & RM=9741,69,34123.29
  8860.415243.0217937.9623343.7328784.8841262.36
River Rch & RM=9741,69,33882.79
 8896.5715306.4118011.7423437.2228900.1741414.55
River Rch & RM=9741,69,33640.75
 8903.0815317.8118025.0223454.0428920.9141441.94
River Rch & RM=9741,69,33400.84
 8916.82 15341.918053.0523489.5628964.7141499.75
River Rch & RM=9741,69,33192.47
 8921.8815350.7718063.3823502.6428980.8441521.04
River Rch & RM=9741,69,32967.68
 8926.5815359.0118072.9723514.7928995.8241540.81
River Rch & RM=9741,69,32726.91
 9049.1215573.8218322.9823831.4829386.3342055.89
River Rch & RM=9741,69,32479.48
 9057.4315588.3918339.9423852.9629412.81 42090.8
River Rch & RM=9741,69,31961.21
 9074.4115618.1718374.5923896.8429466.9342162.13
River Rch & RM=9741,69,31747.18
 9095.3715654.9118417.3523950.99 29533.742250.13
River Rch & RM=9741,69,31503.08
 9706.2416726.6519664.11 25528.431478.7844806.85
River Rch & RM=9741,69,31258.99
 9766.0516831.6619786.2125682.75 31669.145056.33
River Rch & RM=9741,69,31014.89
  9780.116856.33 19814.9   2571931713.8145114.92
River Rch & RM=9741,69,30770.79
 9794.5116881.6319844.3225756.1831759.6645174.99
River Rch & RM=9741,69,30526.69
 9811.0816910.7219878.1525798.9431812.3745244.06
River Rch & RM=9741,69,30282.59
 9905.0717075.7820070.0526041.4332111.3945635.66
River Rch & RM=9741,69,30038.49
 9911.9117087.7920084.0226059.0832133.1545664.15
River Rch & RM=9741,69,29794.39
 9921.99 17105.520104.6126085.0932165.2245706.13
River Rch & RM=9741,69,29550.29
 9947.9117151.0220157.5326151.9532247.6745814.04
River Rch & RM=9741,69, 29306.2
 9949.3517153.5520160.4726155.6632252.2545820.03
River Rch & RM=9741,69,   29212
 9959.0717170.6220180.3226180.7432283.1745860.49
River Rch & RM=9741,69,28887.05
 9976.3517200.97 20215.6 26225.332338.13 45932.4
River Rch & RM=9741,69,28428.97
10027.8217291.3820320.6926358.0532501.8246146.53
River Rch & RM=9741,69,27794.03
10050.1317330.5720366.25 26415.632572.7746239.32
River Rch & RM=9741,69, 26764.9
10774.9118604.6121846.6728283.5834876.1649243.17
River Rch & RM=9741,69,26397.78
10832.6818706.23 21964.728432.3635059.6249481.73
River Rch & RM=9741,69,25901.75
10849.1818735.2621998.4228474.8635112.0249549.86
River Rch & RM=9741,69,25682.29
10866.0418764.9222032.8728518.2835165.5649619.46
River Rch & RM=9741,69,25236.32
10877.5218785.1122056.3228547.8435202.0149666.83
River Rch & RM=9741,69,24857.27
10925.5818869.6722154.53 28671.635354.6349865.14
River Rch & RM=9741,69,24015.93
10965.3918939.7122235.87 28774.135481.0150029.33
River Rch & RM=9741,69,23457.91
11811.0920428.7923964.4530950.0638164.1653504.27
River Rch & RM=9741,69, 22497.1
11857.2120510.0524058.7431068.6238310.3753693.05
River Rch & RM=9741,69,21936.06
11865.4320524.5424075.5531089.7638336.4353726.71
River Rch & RM=9741,69,21017.12
11976.2220719.7824302.0831374.5738687.6354179.93
River Rch & RM=9741,69,20173.44
12134.1120998.0924624.9531780.3939188.0354825.14
River Rch & RM=9741,69,20020.06
12138.0421005.0124632.9831790.4839200.4854841.18
River Rch & RM=9741,69,19390.62
12174.4621069.2324707.4731884.0939315.9154989.91
River Rch & RM=9741,69,18599.67
18222.8531775.4437096.9947364.1358404.1779178.72
River Rch & RM=9741,69,18518.21
 18223.931777.3137099.1547366.8258407.4879182.85
River Rch & RM=9741,69,17693.21
18240.4131806.6437133.0347408.9358459.41 79247.7
River Rch & RM=9741,69,16651.84
 18361.632021.9337381.6347717.9758840.4879723.45
River Rch & RM=9741,69,15757.48
18386.5432066.2337432.7947781.5558918.89 79821.3
River Rch & RM=9741,69,15024.05
18405.8532100.5537472.4147830.8158979.6379897.09
River Rch & RM=9741,69, 14296.1
20489.4335806.14 41748.753138.1865524.0988029.27
River Rch & RM=9741,69, 13325.5
21246.6237154.5743303.5955064.3567899.2390964.48
River Rch & RM=9741,69,12494.01
21256.3937171.9943323.6655089.2167929.8891002.31
River Rch & RM=9741,69,11549.48
21380.3337392.7943578.2155404.3768318.4991481.77
River Rch & RM=9741,69,11358.65
21700.6937963.6344236.2256218.8169322.7892719.82
River Rch & RM=9741,69,10433.17
 21815.838168.7944472.6856511.4169683.5893164.27
River Rch & RM=9741,69, 9491.75
21840.2238212.3144522.8456573.47 69760.1 93258.5
River Rch & RM=9741,69, 8663.77
21852.4238234.0644547.91 56604.569798.3693305.61
River Rch & RM=9741,69,8542.378
21854.5138237.7944552.2156609.8169804.9193313.68
River Rch & RM=9741,69,7056.365
21884.5138291.2544613.8256686.0469898.9193429.43
River Rch & RM=9741,69,5354.459
21967.8638439.8144785.0456897.8670160.1193750.98
River Rch & RM=9741,69,4445.815
23920.9841924.1848798.6961857.5176275.79101253.7
River Rch & RM=9741,69,3583.762
23952.6141980.6448863.6961937.7476374.73101374.6
River Rch & RM=9741,69,2497.592
23968.94 42009.848897.2761979.1876425.83101437.1
River Rch & RM=9741,69,1493.309
25728.4445153.4352515.2366440.4381926.94108144.3
River Rch & RM=9741,69, -0.3901
25803.9645288.4652670.5766631.8182162.93108431.2
Boundary for River Rch & Prof#=9741,69,1
Up Type= 0
Dn Type= 2
Boundary for River Rch & Prof#=9741,69,2
Up Type= 0
Dn Type= 2
Boundary for River Rch & Prof#=9741,69,2
Up Type= 0
Dn Type= 2
Boundary for River Rch & Prof#=9741,69,2
Up Type= 0
Dn Type= 2
Boundary for River Rch & Prof#=9741,69,2
Up Type= 0
Dn Type= 2
Boundary for River Rch & Prof#=9741,69,2
Up Type= 0
Dn Type= 2

--- 9741_ras.g01 (geometry) ---

Geom Title=9741
Program Version=4.10

River Reach=9741,69
Reach XY= 30
854796.268377188777744.064382927854926.260154329777384.977866188
855630.401157942777237.967087669 856528.81752299776744.899669439
856648.157093356776197.338976082 857350.54862494776154.868395427
858868.641454565775026.183311094859948.598548209774833.766885088
860567.216919282774369.129158287861228.506236401774673.083872069
861768.973417352775165.639629723862344.754243913775096.869729458
862389.925643272774642.035432065863011.038532785 773945.74006264
863082.934830853772212.996363763863242.243373176771802.298853632
864056.657952074772038.583211119864354.197271282771989.683359127
865152.545360607771217.233989955865796.439754293771015.120522793
866701.677841811769742.793129608 867096.69454941769474.266182763
868003.627290232769245.034270645869035.468524975769243.661948481
870895.066491658768790.631092938871980.852352041767862.460216417
877310.510283868764336.919844768878440.811455221 763426.20297281
879996.143366364 762511.59268413882668.307038459760566.055941162

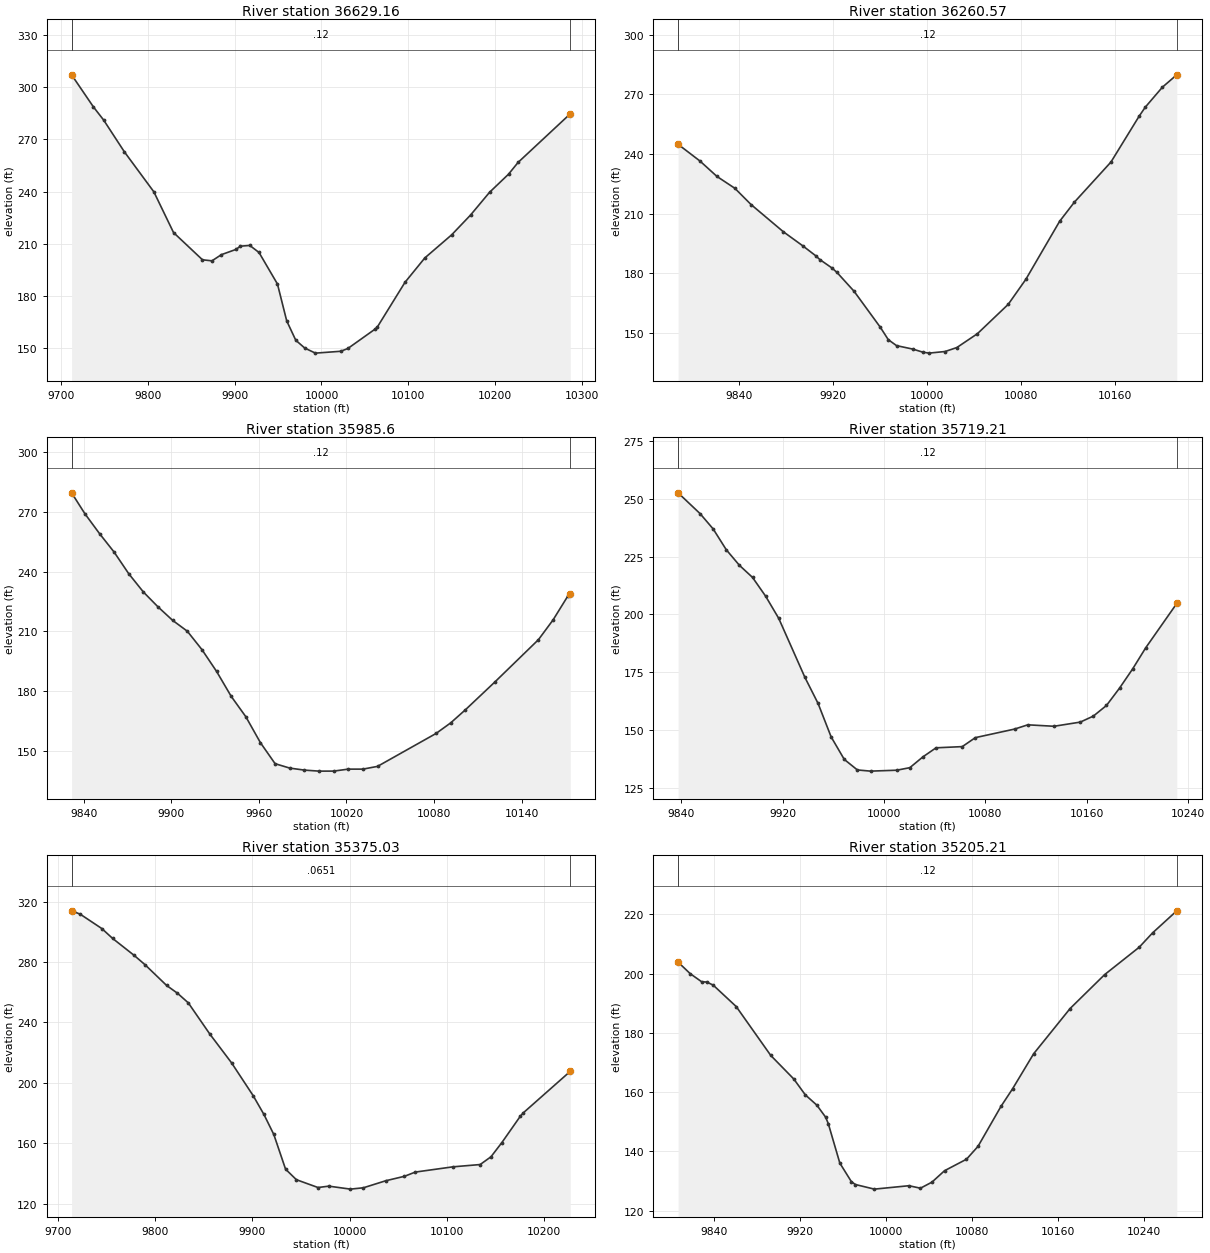
Type RM Length L Ch R = 1 ,36629.16,368.591200,368.591200,368.591200
XS GIS Cut Line= 6
855056.204475628777864.698047994854941.168129342777797.751482178
854879.887209856777770.633446346854720.183477074 777719.34313047
854651.217460671777692.219993384 854531.00967297777635.979278746
#Sta/Elev= 30
9711.932307.19359737.098 288.7279748.967 281.1189772.704262.94799806.767239.8828
9829.446216.45869862.811200.79099873.747200.19619884.682203.76339901.353206.7499
9906.553208.62189917.344209.05499927.983205.00419949.263186.84349959.903165.6788
 9970.36154.51389980.768150.00369993.007147.104310022.32148.173310030.41 149.773
10062.12161.035910064.34162.076210096.28187.840810119.16201.872710150.01215.1229
10171.83226.522510193.73239.605610215.62250.026910226.64 256.80310286.81284.7793
#Mann= 3 , 0 , 0
9711.932    0.12       09711.932    0.12       010286.81    0.12       0
#XS Ineff= 2 , 0
       0                               0
Bank Sta=9711.932,10286.81
Exp/Cntr=0.3,0.1

Type RM Length L Ch R = 1 ,36260.57,274.968000,274.968000,274.968000
XS GIS Cut Line= 2
855057.716255109777550.119099709854766.610865831777241.684095794
#Sta/Elev= 30
9788.108244.85419806.634236.49769821.204228.68719836.399222.74739850.149214.5899
 9877.65200.89619894.049193.88039905.152188.84649908.619186.95069918.902182.7256
9923.188180.49379937.757171.01069960.154152.85729966.895 146.6529973.905143.6725
9987.655 141.9379996.034140.429410001.41139.903410015.16 140.71510025.17142.7041
10042.66149.653310068.88164.418310083.91177.029810112.59206.150110125.16215.7855
10156.29235.974310180.16258.931110185.43263.5019   10200 273.56210212.22279.7799
#Mann= 3 , 0 , 0
9788.108    0.12       09788.108    0.12       010212.22    0.12       0
#XS Ineff= 2 , 0
       0                               0
Bank Sta=9788.108,10212.22
Exp/Cntr=0.3,0.1

Type RM Length L Ch R = 1 , 35985.6,266.391400,266.391400,266.391400
XS GIS Cut Line= 2
855181.681081514777484.081859437855157.996349474777143.269760858
#Sta/Elev= 30
9831.716279.5387 9840.82269.04789850.844259.05659860.868249.74449870.892238.8697
9880.916229.6947 9890.94222.21999900.964215.45119910.989210.01629921.013200.7656
9931.037189.82189941.061177.28359951.085167.04579961.109153.97939971.133143.4578
9981.157141.24339991.181140.232310001.21139.718910011.23139.731910021.25140.7232
10031.28140.7213 10041.3142.1038 10081.4158.641610091.42163.954110101.45170.4973
10121.49184.362810151.57205.783910161.59215.715110171.62227.598610173.35228.7272
#Mann= 3 , 0 , 0
9831.716    0.12       09831.716    0.12       010173.35    0.12       0
#XS Ineff= 2 , 0
       0                               0
Bank Sta=9831.716,10173.35
Exp/Cntr=0.3,0.1

Type RM Length L Ch R = 1 ,35719.21,344.176900,344.176900,344.176900
XS GIS Cut Line= 2
855475.089278206777451.788516196855374.799682636777071.372643871
#Sta/Elev= 30
9837.546252.55019854.908243.5541 9865.25236.92099875.591227.92839885.933221.2185
9896.275215.99169906.616 207.8749916.958198.28129937.641172.74149947.983 161.533
9958.325147.02499968.666137.33319979.008132.7823 9989.35132.277110010.03132.6712
10020.37133.769610030.72138.447710041.06142.353610061.74142.870110072.08146.7547
10103.11150.463710113.45 152.28810134.13151.664210154.82153.460810165.16156.0627
 10175.5160.645610185.84168.164510196.18176.466410206.52185.618410230.96204.7252
#Mann= 3 , 0 , 0
9837.546    0.12       09837.546    0.12       010230.96    0.12       0
#XS Ineff= 2 , 0
       0                               0
Bank Sta=9837.546,10230.96
Exp/Cntr=0.3,0.1

Type RM Length L Ch R = 1 ,35375.03,169.821800,169.821800,169.821800
XS GIS Cut Line= 2
855865.280610548777412.925512659855642.638257479776951.646953562
#Sta/Elev= 30
9714.411313.90659723.211311.70429745.419302.18839756.523295.65179778.731284.3814
9789.835278.23329812.042264.48859823.146259.3685 9834.25253.01059856.458 232.275
9878.666213.32499900.873 191.5899911.977179.10929922.105165.85529934.185142.9064
9945.289135.93799967.497130.75949978.601131.663810000.81129.692610014.13130.5883
10037.13135.245410056.33138.188710067.43140.978310106.15144.452910134.06145.9673
10145.16151.100110156.26160.426110175.17177.823510178.47180.251710226.61207.6686
#Mann= 3 , 0 , 0
9714.411  0.0651       09714.411  0.0651       010226.61  0.0651       0
#XS Ineff= 2 , 0
       0                               0
Bank Sta=9714.411,10226.61
Exp/Cntr=0.3,0.1

Type RM Length L Ch R = 1 ,35205.21,250.808500,250.808500,250.808500
XS GIS Cut Line= 2
855934.643107172777235.488159406 855766.86622739776802.373615033
#Sta/Elev= 30
9806.225203.86239817.472199.98379828.196197.23419832.921  197.15 9838.92196.1079
9860.369188.87639892.541172.38939913.989164.44649924.713159.09569935.437155.6352
9943.657151.56369946.161149.35059956.885136.07219967.609129.83349971.341128.8565
9989.057127.298110021.23128.448110031.95127.609210042.68129.652510054.39133.5029
10074.85137.385310085.57141.716810107.02155.234910117.75161.122810137.45172.9827
10171.37188.218110203.54199.652310235.71208.881910248.18213.7275 10270.7221.1657
#Mann= 3 , 0 , 0
9806.225    0.12       09806.225    0.12       0 10270.7    0.12       0
#XS Ineff= 2 , 0
       0                               0
Bank Sta=9806.225,10270.7
Exp/Cntr=0.3,0.1

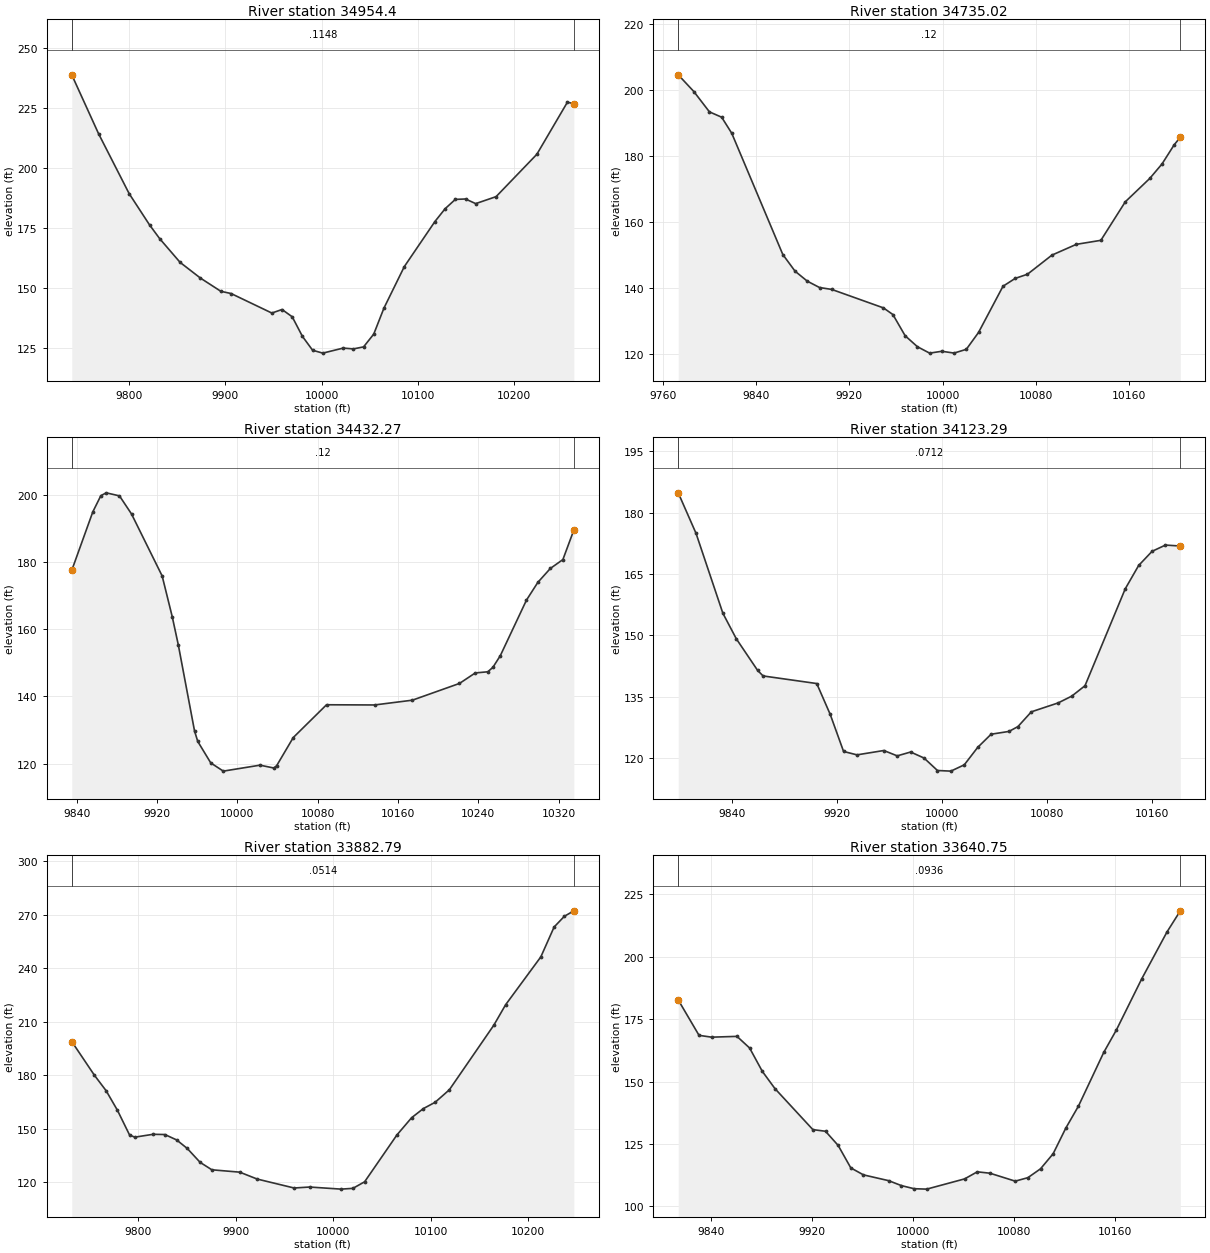
Type RM Length L Ch R = 1 , 34954.4,219.383200,219.383200,219.383200
XS GIS Cut Line= 2
856147.217007869777151.294618089855973.852839408776658.705916305
#Sta/Elev= 30
9740.221238.74419768.097214.20189799.901189.23669821.103176.20959831.704170.4511
9852.907160.58559874.109154.02419895.312148.52829905.913147.60759948.318139.4734
9958.919140.94949969.521137.90619980.122129.75269990.723123.968310001.32122.7688
10022.53124.872510033.13124.530610043.73125.367510054.33130.713810064.93141.5497
10086.13158.846510117.94177.612210128.54182.946810139.14186.828710149.74187.0055
10160.34185.072110181.55187.980410223.95205.632410255.75227.353810262.43 226.685
#Mann= 3 , 0 , 0
9740.221  0.1148       09740.221  0.1148       010262.43  0.1148       0
#XS Ineff= 2 , 0
       0                               0
Bank Sta=9740.221,10262.43
Exp/Cntr=0.3,0.1

Type RM Length L Ch R = 1 ,34735.02,302.747800,302.747800,302.747800
XS GIS Cut Line= 2
856329.110386735777030.496735191856196.742177727776620.043269859
#Sta/Elev= 30
 9772.97204.66279786.362 199.593 9799.76193.42149810.267191.79639818.943186.9191
9862.803150.1085 9873.31 145.0539883.817142.02349894.324140.09089904.831139.5111
9949.267133.90229957.367131.87969967.874125.45179978.381122.12769988.888120.1726
9999.395120.7345 10009.9120.188410020.41121.325210030.92126.448610051.93140.4738
10062.44142.866110072.95144.123210093.96149.927110114.97153.204410135.99154.4164
   10157 166.12410178.02 173.21510188.52177.603710199.03183.450810204.24185.6973
#Mann= 3 , 0 , 0
 9772.97    0.12       0 9772.97    0.12       010204.24    0.12       0
#XS Ineff= 2 , 0
       0                               0
Bank Sta=9772.97,10204.24
Exp/Cntr=0.3,0.1

Type RM Length L Ch R = 1 ,34432.27,308.983700,308.983700,308.983700
XS GIS Cut Line= 6
856670.271462324776834.712454208856653.110307908776818.531419456
856602.034095519776774.276063485856543.145641592776727.957284455
856353.616794657776584.453754273856276.242030884776526.804736116
#Sta/Elev= 30
 9834.91 177.5819855.899195.02099863.889199.82999869.227 200.6799882.459199.7681
9894.431194.38579924.973175.90349935.028163.75269941.082155.34919957.257129.6832
9960.473126.56919973.432120.17429985.919 117.73210022.48119.507610036.29118.6617
10039.06119.343910055.63 127.74410088.77137.511610136.63 137.45210174.27138.8748
10221.26143.870410236.99146.995310249.47 147.34310254.55148.660510261.94152.1396
10288.03168.714210299.35173.989910311.83 178.148 10324.3180.779910335.22189.5885
#Mann= 3 , 0 , 0
 9834.91    0.12       0 9834.91    0.12       010335.22    0.12       0
#XS Ineff= 2 , 0
       0                               0
Bank Sta=9834.91,10335.22
Exp/Cntr=0.3,0.1

Type RM Length L Ch R = 1 ,34123.29,240.497900,240.497900,240.497900
XS GIS Cut Line= 2
856758.267988287776467.638248813856383.938813076 776387.73055514
#Sta/Elev= 30
9799.132184.81339812.699174.90469833.149155.37349843.375149.1319 9859.67141.3814
9863.825140.03239904.727138.17469914.952130.66459925.177121.56169935.402120.7317
9955.853121.79589966.078120.48649976.304121.42719986.529119.95559996.754116.9061
10006.98116.7541 10017.2118.297710027.43122.560610037.66125.780110051.27126.4648
10058.11127.647610068.33131.256610088.78133.437410099.17135.103710109.23137.6404
10139.91161.340710150.13167.046910160.36170.505610170.58172.039610181.89171.8019
#Mann= 3 , 0 , 0
9799.132  0.0712       09799.132  0.0712       010181.89  0.0712       0
#XS Ineff= 2 , 0
       0                               0
Bank Sta=9799.132,10181.89
Exp/Cntr=0.3,0.1

Type RM Length L Ch R = 1 ,33882.79,242.035800,242.035800,242.035800
XS GIS Cut Line= 2
856791.138479669776424.262652572856503.711320425775996.913793068
#Sta/Elev= 30
9732.023199.00729755.237180.12939767.289171.42439778.858160.49259791.391146.5342
9796.776145.41969815.494147.01899827.546146.87769839.597143.85649850.531139.0608
  9863.7131.28069875.751127.11169904.285125.79989922.203121.93199960.111116.9133
9975.958 117.45910008.32116.282310020.37116.711310032.42120.395810065.55146.6446
10080.63156.315910092.68161.428510104.73164.9492 10119.3171.941610164.99208.2011
10177.04219.627810213.19246.479310226.81263.207510237.29269.199510247.04272.2769
#Mann= 3 , 0 , 0
9732.023  0.0514       09732.023  0.0514       010247.04  0.0514       0
#XS Ineff= 2 , 0
       0                               0
Bank Sta=9732.023,10247.04
Exp/Cntr=0.3,0.1

Type RM Length L Ch R = 1 ,33640.75,239.909200,239.909200,239.909200
XS GIS Cut Line= 2
856892.264315543776361.450980794856867.115547271775964.451851201
#Sta/Elev= 30
9814.175182.71629830.659168.51789840.679167.79069860.719168.10749870.739163.4387
9880.759154.11079890.779147.17929920.839130.71949930.859130.06239940.879 124.381
9950.899115.37489960.919112.5738 9980.96110.2411 9990.98108.2723   10001 107.028
10011.02106.857610041.08110.9613 10051.1113.794110061.12113.243810081.16110.0586
10091.18111.4469 10101.2114.999810111.22121.051810121.24131.320910131.26140.1426
 10151.3161.671610161.32170.675510181.36191.1361 10201.4209.965810211.97  218.45
#Mann= 3 , 0 , 0
9814.175  0.0936       09814.175  0.0936       010211.97  0.0936       0
#XS Ineff= 2 , 0
       0                               0
Bank Sta=9814.175,10211.97
Exp/Cntr=0.3,0.1

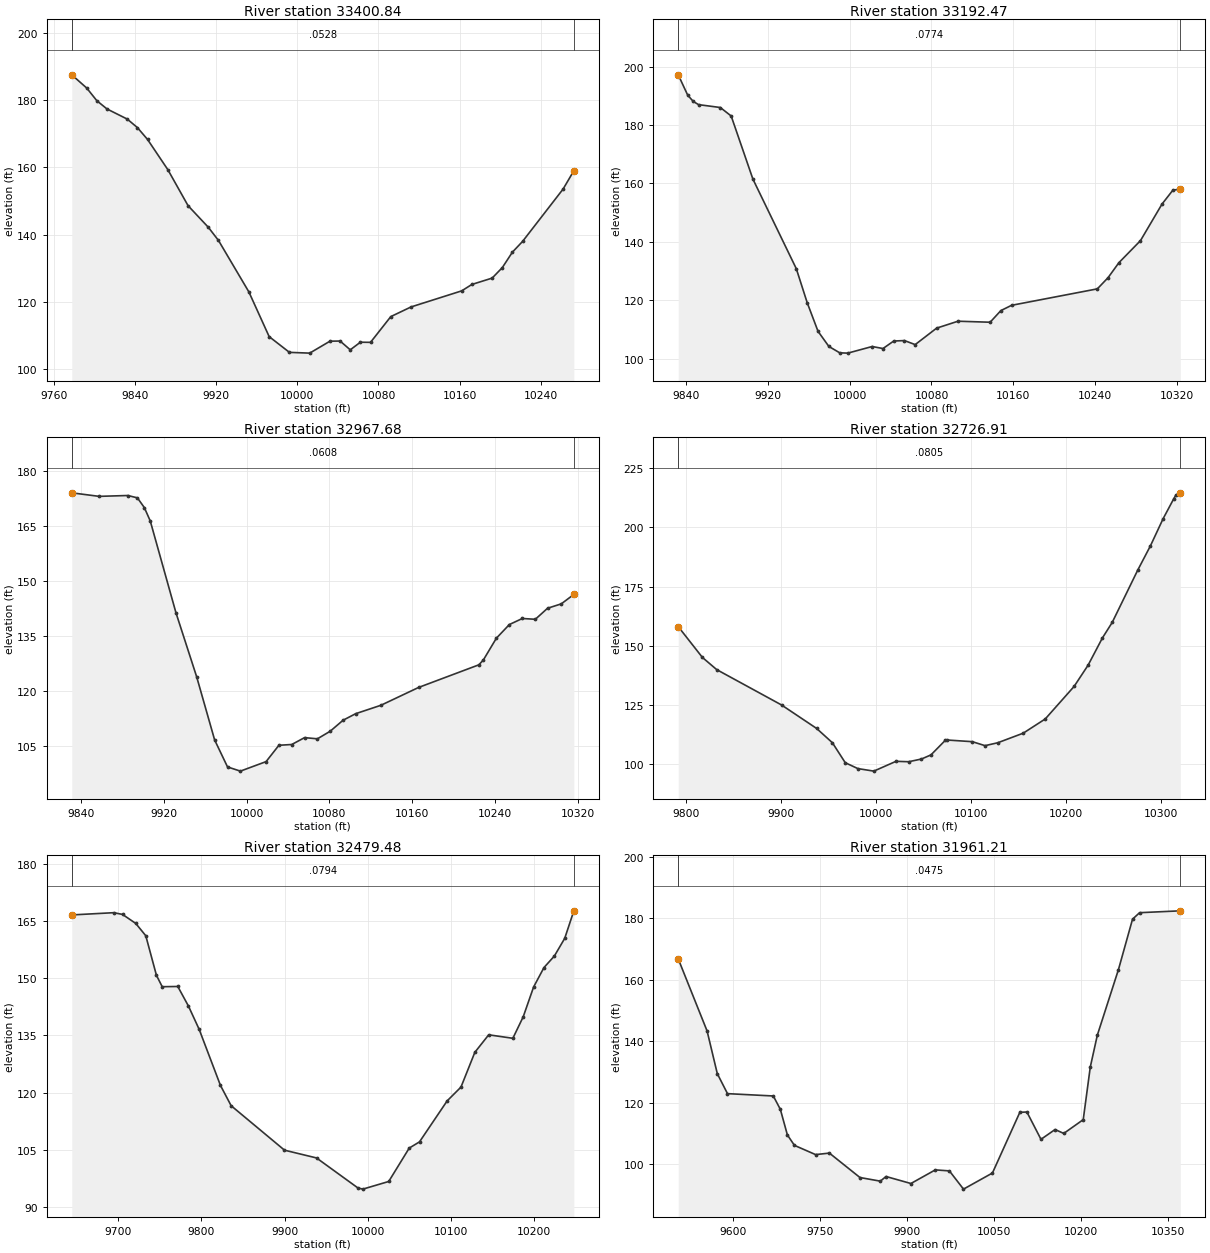
Type RM Length L Ch R = 1 ,33400.84,208.371900,208.371900,208.371900
XS GIS Cut Line= 2
857121.480949961776409.739795152857118.096438049775914.399507009
#Sta/Elev= 30
9777.392187.47329792.132183.55349802.132179.78189812.133177.33439832.133174.3221
9842.133171.80059852.134168.28249872.134159.31129892.134148.58969912.135 142.167
9922.135138.26439952.136122.96489972.136109.68889992.137  105.0110012.14104.7823
10032.14108.332110042.14108.374710052.14105.765610062.14108.024610072.14107.9847
10092.14115.634610112.14118.508310162.14123.286910172.14125.189910192.14127.0762
10202.14 130.18410212.14134.789310222.14137.969610262.14153.535510272.74158.9744
#Mann= 3 , 0 , 0
9777.392  0.0528       09777.392  0.0528       010272.74  0.0528       0
#XS Ineff= 2 , 0
       0                               0
Bank Sta=9777.392,10272.74
Exp/Cntr=0.3,0.1

Type RM Length L Ch R = 1 ,33192.47,224.794000,224.794000,224.794000
XS GIS Cut Line= 6
857380.180022181776323.647095778 857375.83831386776312.267639761
857326.502816472776172.076345311857311.649651306776127.929144935
857258.861378688775955.069347196 857227.09065222775858.027566472
#Sta/Elev= 30
9832.743 197.2129841.998190.24269847.448 188.0849852.628 186.998 9873.83186.0205
9884.431 183.1139905.633161.51519948.038130.80529958.639119.1998 9969.24109.3642
9979.841104.18599990.443102.00419998.275101.901610022.11104.167910032.66103.4747
10043.18 106.05110053.64106.1981 10064.1104.820910085.01110.456410105.92112.8319
10137.29112.483710147.74116.4627 10158.2118.277610241.98123.9133 10252.5127.7741
10263.02132.878510284.07140.426910305.11152.950510315.63 157.67610322.97158.1259
#Mann= 3 , 0 , 0
9832.743  0.0774       09832.743  0.0774       010322.97  0.0774       0
#XS Ineff= 2 , 0
       0                               0
Bank Sta=9832.743,10322.97
Exp/Cntr=0.3,0.1

Type RM Length L Ch R = 1 ,32967.68,240.762300,240.762300,240.762300
XS GIS Cut Line= 6
857615.837788658776186.522090379857584.452151344776142.418401318
857515.802210286776049.432880817857459.388341356 775972.30542083
857417.563327463775911.589623225857329.692479152775795.336209719
#Sta/Elev= 30
9831.287173.96049857.702172.99789885.418173.2305 9894.64172.58969901.332 169.943
 9907.07  166.289931.931141.19229951.839123.80239969.222  106.559981.65299.19338
9994.08398.0488910018.88 100.64410031.27105.101510043.66 105.31110056.05107.1877
10068.44106.860510080.83108.940410093.22111.934910105.43113.722710129.71116.0066
10166.14120.876210224.29127.041710228.69128.385510241.22 134.30810253.76138.0337
10266.29139.682810278.83139.466910290.62142.4734 10303.9143.676510316.01146.2436
#Mann= 3 , 0 , 0
9831.287  0.0608       09831.287  0.0608       010316.01  0.0608       0
#XS Ineff= 2 , 0
       0                               0
Bank Sta=9831.287,10316.01
Exp/Cntr=0.3,0.1

Type RM Length L Ch R = 1 ,32726.91,247.435300,247.435300,247.435300
XS GIS Cut Line= 2
857831.924266946 776046.21828327857480.455499303775651.462878935
#Sta/Elev= 30
9792.136158.10559817.587145.09649832.626139.96059900.881125.03049937.893115.1002
9954.438109.0744 9967.97100.64759981.21798.168659998.04697.0968210021.38101.2352
10034.77101.068410048.16102.2065 10058.2 103.95210073.24110.082610074.94110.2443
10101.72109.530510115.11107.8529 10128.5109.074510155.28113.114910178.51119.1275
10208.83132.837610223.62141.841210238.66153.3227   10249159.890110275.78 181.901
10289.17192.178110302.56203.667910313.85 212.16210315.95213.588810320.68214.6035
#Mann= 3 , 0 , 0
9792.136  0.0805       09792.136  0.0805       010320.68  0.0805       0
#XS Ineff= 2 , 0
       0                               0
Bank Sta=9792.136,10320.68
Exp/Cntr=0.3,0.1

Type RM Length L Ch R = 1 ,32479.48,518.266300,518.266300,518.266300
XS GIS Cut Line= 6
858073.407722961775984.356678614857881.119094536775746.104218081
857852.256239117775706.464778762 857851.10803895775704.827208551
857816.310760744775656.818766876 857703.54384979775506.209009317
#Sta/Elev= 30
9643.797166.55849694.373167.14619704.951166.69219720.874164.32549732.925161.1052
9745.775150.71989752.718147.74299771.477147.80069784.327142.65949797.178136.5821
9822.879121.85299835.729116.53769899.982104.88579938.534102.84979988.44294.97657
9994.33994.6736410025.4996.6773910050.19105.432510062.57107.066210095.85117.8041
10112.53121.430810129.22130.5421 10145.9135.1297   10175134.218310187.49139.8643
10199.98147.666910212.47152.763710224.97155.780210237.46160.422210248.44167.6347
#Mann= 3 , 0 , 0
9643.797  0.0794       09643.797  0.0794       010248.44  0.0794       0
#XS Ineff= 2 , 0
       0                               0
Bank Sta=9643.797,10248.44
Exp/Cntr=0.3,0.1

Type RM Length L Ch R = 1 ,31961.21,214.029900,214.029900,214.029900
XS GIS Cut Line= 3
858583.334247596775859.987052197858099.287713855775159.699889724
858091.090039608775146.886597688
#Sta/Elev= 30
9505.515166.77599555.346143.28459572.933129.4142 9590.52122.9055 9669.61122.1444
9681.766117.78279693.923109.44529706.079106.06479742.548103.06369766.391103.5526
9819.15295.597979854.32694.417099864.11295.931429907.08793.651599949.20698.08705
9973.51997.756549997.83291.8223510047.7897.0683510095.08116.827910107.24116.9276
10131.55108.034710155.86111.221910170.89109.954910204.49 114.44210216.65131.5694
 10228.8 141.93710265.27163.294710289.58179.710610301.74181.810910372.02182.4187
#Mann= 3 , 0 , 0
9505.515  0.0475       09505.515  0.0475       010372.02  0.0475       0
#XS Ineff= 2 , 0
       09849.599         10088.4       0
Bank Sta=9505.515,10372.02
Exp/Cntr=0.3,0.1

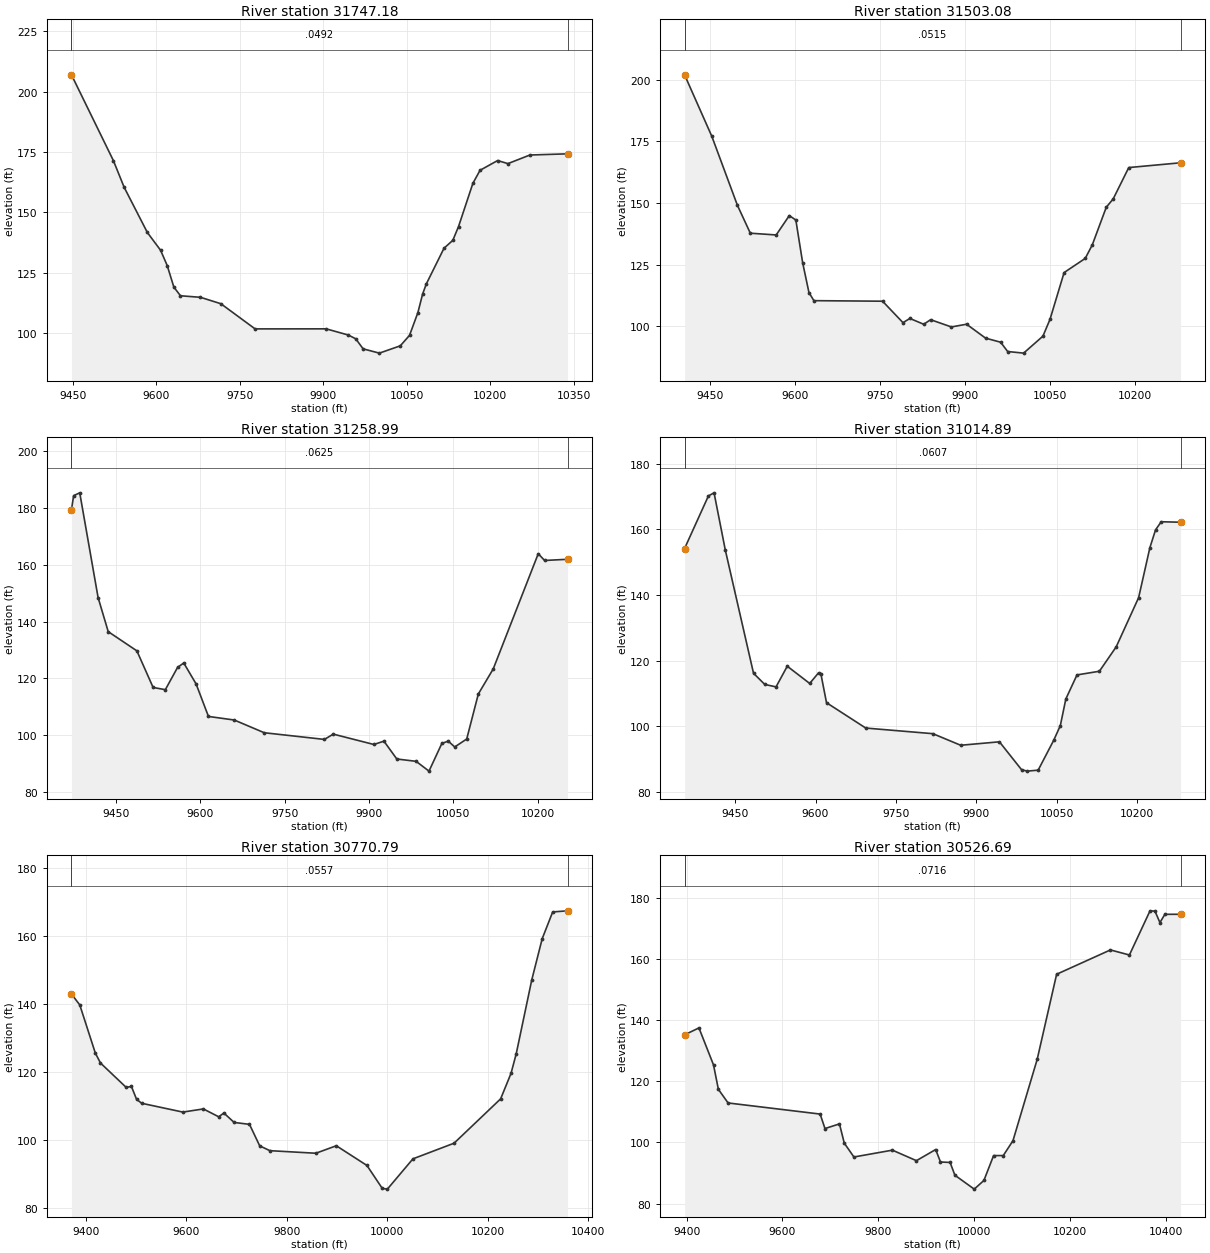
Type RM Length L Ch R = 1 ,31747.18,244.098800,244.098800,244.098800
XS GIS Cut Line= 6
858793.605736936775771.541228498 858676.35921086775583.370879465
 858592.54474569775466.698293467858548.557145165775411.492297701
858350.912380137775181.113656729858261.080760751775058.259399073
#Sta/Elev= 30
9447.375206.92789522.777171.36919542.082160.33479583.762 141.6139607.596134.2357
9619.514127.89989631.431 118.9859643.348115.37919679.335114.73649715.931112.0877
9777.501101.65329905.308101.67279945.18599.101619958.478 97.54179971.77193.37397
   1000191.6096610038.5694.6359410055.1798.96854 10070.2108.398210078.74116.1279
10085.51120.362610117.17135.075110133.01138.354210143.28144.059510169.07161.9669
10181.97167.374610213.54 171.40910232.09170.1387 10271.6173.699510339.19174.1905
#Mann= 3 , 0 , 0
9447.375  0.0492       09447.375  0.0492       010339.19  0.0492       0
#XS Ineff= 2 , 0
       09811.457                       0
Bank Sta=9447.375,10339.19
Exp/Cntr=0.3,0.1

Type RM Length L Ch R = 1 ,31503.08,244.098700,244.098700,244.098700
XS GIS Cut Line= 6
858974.424680183775667.926094842858901.800905534775530.631138117
858863.445126976775464.783060057858789.619194295775348.726788386
858581.343178665775063.395478887858492.513303661774937.599520292
#Sta/Elev= 30
9404.589201.9402 9452.64177.05729497.958  149.039520.755137.73569566.447137.0194
9589.593144.87319601.166143.07469613.178125.79839624.311 113.6899633.046110.3853
9754.396110.16399790.454101.46879802.671103.17059827.107100.81789839.325102.6697
9875.97899.728989902.851100.83259936.43795.186739962.97293.541329975.41989.76674
10003.6189.1153610037.7195.9945710050.18102.788810075.11121.7676 10112.5127.5198
10124.97133.0206 10149.6148.2415 10161.9151.655510189.37164.347210280.98166.2822
#Mann= 3 , 0 , 0
9404.589  0.0515       09404.589  0.0515       010280.98  0.0515       0
#XS Ineff= 2 , 0
       09748.489                       0
Bank Sta=9404.589,10280.98
Exp/Cntr=0.3,0.1

Type RM Length L Ch R = 1 ,31258.99,244.098800,244.098800,244.098800
XS GIS Cut Line= 6
 859130.64496409775598.524330949859056.494193713775424.760259726
859011.425852501775325.300171346858966.455247247775230.892735279
858903.409291184775107.637042634858739.049208856774809.066518853
#Sta/Elev= 30
9370.999179.3673 9374.83184.35799385.703185.3557 9418.32148.47089436.338136.4441
9487.294129.67389516.172116.77339537.917115.99739559.662123.84649570.638125.4003
9592.596118.02039614.553106.56249660.457105.30359713.756100.82159820.80298.46715
9836.468100.33379908.63996.684199926.58997.850629949.46991.568479983.78890.74739
10006.6987.2945910029.5497.0403810040.9797.87946 10052.495.8024910073.7498.60062
10094.41114.478110120.96123.330910200.93163.890210212.26161.521410252.96161.9362
#Mann= 3 , 0 , 0
9370.999  0.0625       09370.999  0.0625       010252.96  0.0625       0
#XS Ineff= 2 , 0
       09648.585                       0
Bank Sta=9370.999,10252.96
Exp/Cntr=0.3,0.1

Type RM Length L Ch R = 1 ,31014.89,244.098800,244.098800,244.098800
XS GIS Cut Line= 6
859271.759641691775557.273011339859221.587786931775404.843567055
859145.158524784775158.769667042859066.109171013774863.443798488
859025.173936728 774730.51261306859004.082492899774670.891153419
#Sta/Elev= 30
9355.536154.2003 9400.04170.22919410.567171.17459431.623153.70179484.262116.1594
9505.317112.75169526.317112.0101 9547.26118.31079589.145113.06129605.647116.2785
9610.087115.96239620.558107.18529693.85799.456179819.14397.742769871.07894.21131
9943.42995.264239984.73286.762679995.05786.3248210015.7386.6176710044.7295.70096
10057.12100.184410067.46 108.33910088.25115.6563 10130.1116.7768 10161.5124.2219
10203.35139.220210224.35154.445810234.96159.884510245.57162.356910281.75162.2109
#Mann= 3 , 0 , 0
9355.536  0.0607       09355.536  0.0607       010281.75  0.0607       0
#XS Ineff= 2 , 0
       09601.838                       0
Bank Sta=9355.536,10281.75
Exp/Cntr=0.3,0.1

Type RM Length L Ch R = 1 ,30770.79,244.098700,244.098700,244.098700
XS GIS Cut Line= 6
 859450.92877183775511.062337376 859408.04175956775327.339136836
859375.036594315775164.197701379 859313.95493785774829.827009514
859291.840494835774730.332334462859242.261180754774546.717658475
#Sta/Elev= 30
9371.243142.88139387.807139.66219418.721125.49589428.977122.5737 9480.26115.3748
9490.517 115.6839500.773111.8863 9511.03110.71239592.908108.12079633.718 109.049
9664.326106.73259674.529107.84859694.934105.07189725.542 104.5119745.87198.17167
9766.19796.759929857.66496.004419898.31698.209599959.29492.402879989.78385.64812
9999.94585.4385110050.8294.3560110132.6798.9613510225.32112.016510245.97 119.506
10256.29125.241910287.26147.026710308.08159.183410328.93167.0498 10358.4167.3765
#Mann= 3 , 0 , 0
9371.243  0.0557       09371.243  0.0557       0 10358.4  0.0557       0
#XS Ineff= 2 , 0
       0                10148.76       0
Bank Sta=9371.243,10358.4
Exp/Cntr=0.3,0.1

Type RM Length L Ch R = 1 ,30526.69,244.098800,244.098800,244.098800
XS GIS Cut Line= 6
859635.199720349775434.536993671859603.926718733 775247.45488178
859566.433258223774863.448880101859540.642843818774682.774415001
859518.049534696774567.057142553859476.672676899774413.650281888
#Sta/Elev= 30
 9395.73135.15219425.701137.40929456.113125.3093 9466.25117.33579486.525112.8857
9678.564109.25659688.639104.52319718.866106.04829728.94199.751559749.03995.23027
9829.30397.467779879.46894.02923  9919.697.670839929.63393.599259949.69993.44932
9959.73289.2724910000.0484.7323510020.2487.5626610040.4495.6863910060.6595.70092
10080.86100.547210131.37127.110710171.94154.937910284.19 162.88610323.83161.2349
10366.82 175.66410377.15175.563210387.48171.823310397.81174.526710430.65174.5295
#Mann= 3 , 0 , 0
 9395.73  0.0716       0 9395.73  0.0716       010430.65  0.0716       0
#XS Ineff= 2 , 0
       0                               0
Bank Sta=9395.73,10430.65
Exp/Cntr=0.3,0.1

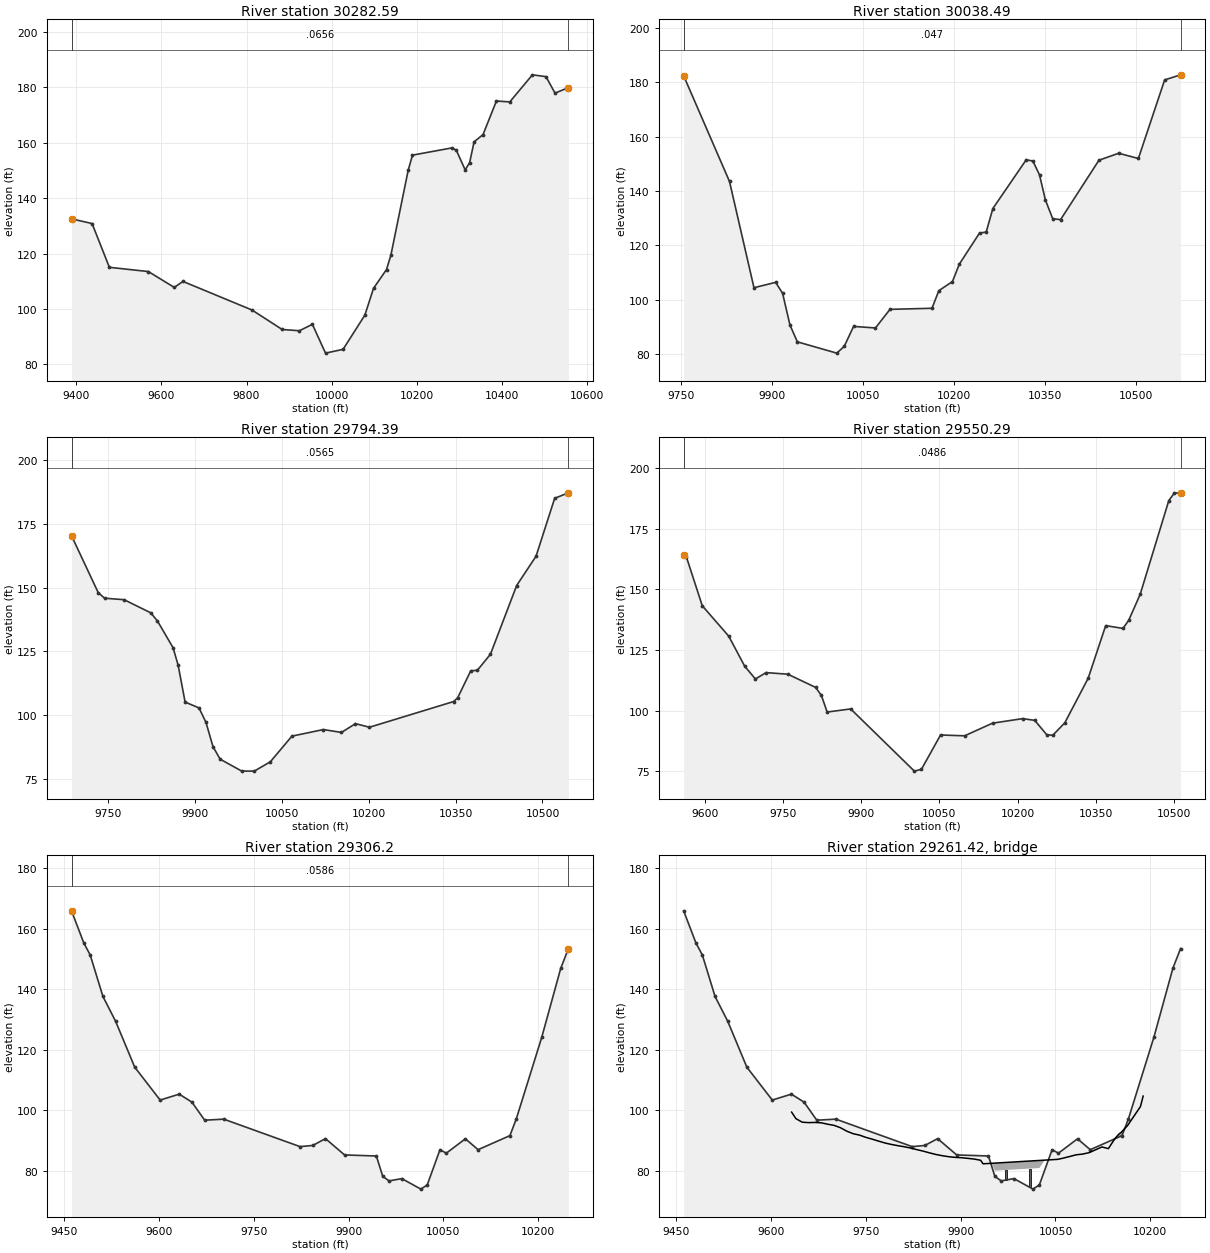
Type RM Length L Ch R = 1 ,30282.59,244.098700,244.098700,244.098700
XS GIS Cut Line= 6
859904.883902715775452.465163492859813.599730814 774903.94480173
859788.817358987774802.226972827859761.310829801774648.892673302
859701.794645158774439.853014832859657.304941627774315.327507487
#Sta/Elev= 30
 9389.21132.53099437.443130.8408 9478.09115.03399569.546  113.519630.444107.7786
9650.737109.94759812.82299.621959883.595 92.60129924.03792.143469954.51594.46189
9985.33884.0642210026.55 85.428810077.6897.77476   10098107.442210128.48114.2433
10138.64119.332410179.28149.994410189.44 155.52910281.98158.142710292.29 157.317
10313.14150.190210323.61 152.85610334.08160.344910355.02 162.94410386.43175.0681
10417.84174.741810470.86184.517310502.72183.863810523.96177.914810555.47179.8963
#Mann= 3 , 0 , 0
 9389.21  0.0656       0 9389.21  0.0656       010555.47  0.0656       0
#XS Ineff= 2 , 0
       0                               0
Bank Sta=9389.21,10555.47
Exp/Cntr=0.3,0.1

Type RM Length L Ch R = 1 ,30038.49,244.098800,244.098800,244.098800
XS GIS Cut Line= 6
860148.959852689774976.733397358860092.103382257774868.975990817
859967.691808901774707.377969194859935.946602696774655.388487931
859854.350206917774487.481851212859757.781099444774260.771334636
#Sta/Elev= 30
9753.906182.41229829.593143.50349869.986104.42099905.786 106.3899917.224102.3466
9929.40690.669019941.58884.4988110006.63 80.348910018.9482.8335910034.37 90.1772
10070.48  89.61110094.4696.4546510163.81 96.850810175.06103.331810197.56106.6844
10208.81113.058110242.22124.530110253.23124.905510264.25133.562110319.32151.4967
10330.31151.016910341.22145.943410350.99136.665510363.04129.8117   10376129.4654
10439.33 151.32510471.86153.887310504.39151.960610547.76180.873610574.03182.7469
#Mann= 3 , 0 , 0
9753.906   0.047       09753.906   0.047       010574.03   0.047       0
#XS Ineff= 2 , 0
       0                               0
Bank Sta=9753.906,10574.03
Exp/Cntr=0.3,0.1

Type RM Length L Ch R = 1 ,29794.39,244.098700,244.098700,244.098700
XS GIS Cut Line= 6
860376.830953469774896.953163969860350.663401624774838.882323418
860304.674760897774756.982980346860088.208408442774446.964118211
860022.542710457774337.004399885859934.588701672774164.769496014
#Sta/Elev= 30
9687.469170.25889733.485148.03689744.454145.82789778.197145.24299824.209140.1036
9835.812136.8907 9862.66126.46199871.465119.60119883.452105.20259907.426102.9286
9919.41397.29037 9931.5387.790679943.88882.879839980.96378.2365910002.7478.20213
10030.51 81.848110067.7291.8816510121.9594.4563510153.2493.3305210177.3996.76425
10201.5395.3643710346.59105.406710353.65106.862210376.28117.4449 10387.6117.6173
10410.24123.920210455.49150.794110488.92162.248110521.05184.8943 10544.8187.0359
#Mann= 3 , 0 , 0
9687.469  0.0565       09687.469  0.0565       0 10544.8  0.0565       0
#XS Ineff= 2 , 0
       0                               0
Bank Sta=9687.469,10544.8
Exp/Cntr=0.3,0.1

Type RM Length L Ch R = 1 ,29550.29,244.098800,244.098800,244.098800
XS GIS Cut Line= 6
860572.933480634774890.315181546860541.731453726774726.165201083
 860493.78760295774602.687331933860303.982725643774332.452461923
860213.545562473 774165.90983329860158.738767797774044.214947394
#Sta/Elev= 30
9559.258164.2271 9564.63163.22829594.974143.17659645.669 130.6699676.409118.2459
9696.902112.99129717.396115.62249759.229114.95669812.611109.51059823.602106.1943
9834.59499.366759879.759100.650110001.9375.0162410015.4275.75153 10052.289.91955
10098.2889.5654410151.9894.7848110209.7496.6566210232.8295.9394110255.8990.02232
10267.4389.7892210290.51 94.915610335.38113.2897   10369 134.98610402.16133.8282
10413.15137.170810435.13147.845810490.06186.504410500.96189.712110512.66189.5311
#Mann= 3 , 0 , 0
9559.258  0.0486       09559.258  0.0486       010512.66  0.0486       0
#XS Ineff= 2 , 0
       09866.495                       0
Bank Sta=9559.258,10512.66
Exp/Cntr=0.3,0.1

Type RM Length L Ch R = 1 , 29306.2,94.197800,94.197800,94.197800
XS GIS Cut Line= 2
860676.298892663774904.389866784 860589.70222482774122.962845446
#Sta/Elev= 30
 9461.68165.99159481.188155.32779491.249 151.3939511.372137.65889531.494129.4219
9561.678114.26479601.923103.37499632.106105.33679652.229102.68659672.35196.71342
9702.53597.05998 9823.2787.967129843.39288.358999863.51490.614799893.69885.21779
9944.004 84.86839954.06578.139949964.12776.623159984.24977.3896810014.4373.90546
10024.4975.3004510044.6286.9369310054.6885.8006510084.8690.5592910104.9886.95618
10155.2991.6104410165.3597.11392 10205.6124.101410235.78147.014910247.89153.5138
#Mann= 3 , 0 , 0
 9461.68  0.0586       0 9461.68  0.0586       010247.89  0.0586       0
#XS Ineff= 2 , 0
       09706.701        10108.98       0
Bank Sta=9461.68,10247.89
Exp/Cntr=0.3,0.1

Type RM Length L Ch R = 3 ,29261.42,,,
BEGIN DESCRIPTION:
END DESCRIPTION:
Bridge Culvert--1,0,-1,-1, 0
Deck Dist Width WeirC Skew NumUp NumDn MinLoCord MaxHiCord MaxSubmerge Is_Ogee
36.098900,22.000000,2.6,0, 58, 58, , , 0.95, 0, 0,0,,
 9632.52 9639.24 9649.32 9659.40 9669.48 9679.56 9689.64 9699.72 9705.17 9709.80
 9719.88 9729.96 9740.04 9750.12 9760.20 9770.28 9780.36 9784.58 9790.44 9800.52
 9810.60 9820.68 9830.76 9840.84 9850.92 9861.00 9863.98 9871.08 9881.16 9891.24
 9899.71 9901.32 9911.40 9921.48 9931.56 9935.41 9935.91 9935.9110045.9110045.91
10053.1610060.9510062.6010072.7510082.9010092.1910093.0510103.2010113.3610123.51
10133.6610143.8110150.1510153.9710164.1210174.2710184.4210188.70
   99.38   97.24   96.05   95.91   95.97   95.84   95.38   95.00   94.58   94.22
   93.07   92.24   91.77   91.02   90.43   89.78   89.16   88.96   88.69   88.29
   87.93   87.50   86.97   86.47   85.89   85.36   85.24   84.96   84.63   84.41
   84.32   84.30   84.08   83.85   83.45   82.28   82.29   82.29   83.66   83.66
   83.75   84.09   84.18   84.72   85.27   85.48   85.51   85.97   86.92   87.86
   87.30   90.57   92.08   92.70   94.97   98.09  101.22  104.69
 -900.62 -902.76 -903.95 -904.09 -904.03 -904.16 -904.62 -905.00 -905.42 -905.78
 -906.93 -907.76 -908.23 -908.98 -909.57 -910.22 -910.84 -911.04 -911.31 -911.71
 -912.07 -912.50 -913.03 -913.53 -914.11 -914.64 -914.76 -915.04 -915.37 -915.59
 -915.68 -915.70 -915.92 -916.15 -916.55 -917.72 -917.71   79.79   81.16 -916.34
 -916.25 -915.91 -915.82 -915.28 -914.73 -914.52 -914.49 -914.03 -913.08 -912.14
 -912.70 -909.43 -907.92 -907.30 -905.03 -901.91 -898.78 -895.31
 9632.52 9639.24 9649.32 9659.40 9669.48 9679.56 9689.64 9699.72 9705.17 9709.80
 9719.88 9729.96 9740.04 9750.12 9760.20 9770.28 9780.36 9784.58 9790.44 9800.52
 9810.60 9820.68 9830.76 9840.84 9850.92 9861.00 9863.98 9871.08 9881.16 9891.24
 9899.71 9901.32 9911.40 9921.48 9931.56 9935.41 9940.62 9940.6210050.6210050.62
10053.1610060.9510062.6010072.7510082.9010092.1910093.0510103.2010113.3610123.51
10133.6610143.8110150.1510153.9710164.1210174.2710184.4210188.70
   99.38   97.24   96.05   95.91   95.97   95.84   95.38   95.00   94.58   94.22
   93.07   92.24   91.77   91.02   90.43   89.78   89.16   88.96   88.69   88.29
   87.93   87.50   86.97   86.47   85.89   85.36   85.24   84.96   84.63   84.41
   84.32   84.30   84.08   83.85   83.45   82.28   82.35   82.35   83.72   83.72
   83.75   84.09   84.18   84.72   85.27   85.48   85.51   85.97   86.92   87.86
   87.30   90.57   92.08   92.70   94.97   98.09  101.22  104.69
 -900.62 -902.76 -903.95 -904.09 -904.03 -904.16 -904.62 -905.00 -905.42 -905.78
 -906.93 -907.76 -908.23 -908.98 -909.57 -910.22 -910.84 -911.04 -911.31 -911.71
 -912.07 -912.50 -913.03 -913.53 -914.11 -914.64 -914.76 -915.04 -915.37 -915.59
 -915.68 -915.70 -915.92 -916.15 -916.55 -917.72 -917.65   79.85   81.22 -916.28
 -916.25 -915.91 -915.82 -915.28 -914.73 -914.52 -914.49 -914.03 -913.08 -912.14
 -912.70 -909.43 -907.92 -907.30 -905.03 -901.91 -898.78 -895.31
Pier Skew, UpSta & Num, DnSta & Num=  ,9972.08, 2 ,9976.79, 2 , 0 , 0 , 0 ,,
    3.00    3.00
 -917.26   82.74
    3.00    3.00
 -917.20   82.80
Pier Skew, UpSta & Num, DnSta & Num=  ,10009.74, 2 ,10014.46, 2 , 0 , 0 , 0 ,,
    3.00    3.00
 -916.79   83.21
    3.00    3.00
 -916.73   83.27
BR Coef=-1 , 0 , 0 ,, 0 ,,,0.8,0,1,0,
WSPro=,,,, 1 ,,,, 0 ,,,, 0 ,,,,-1 ,-1 ,-1 , 0 , 0 , 0 , 0 , 0
BC Design=,, 0 ,, 0 ,,,,,,