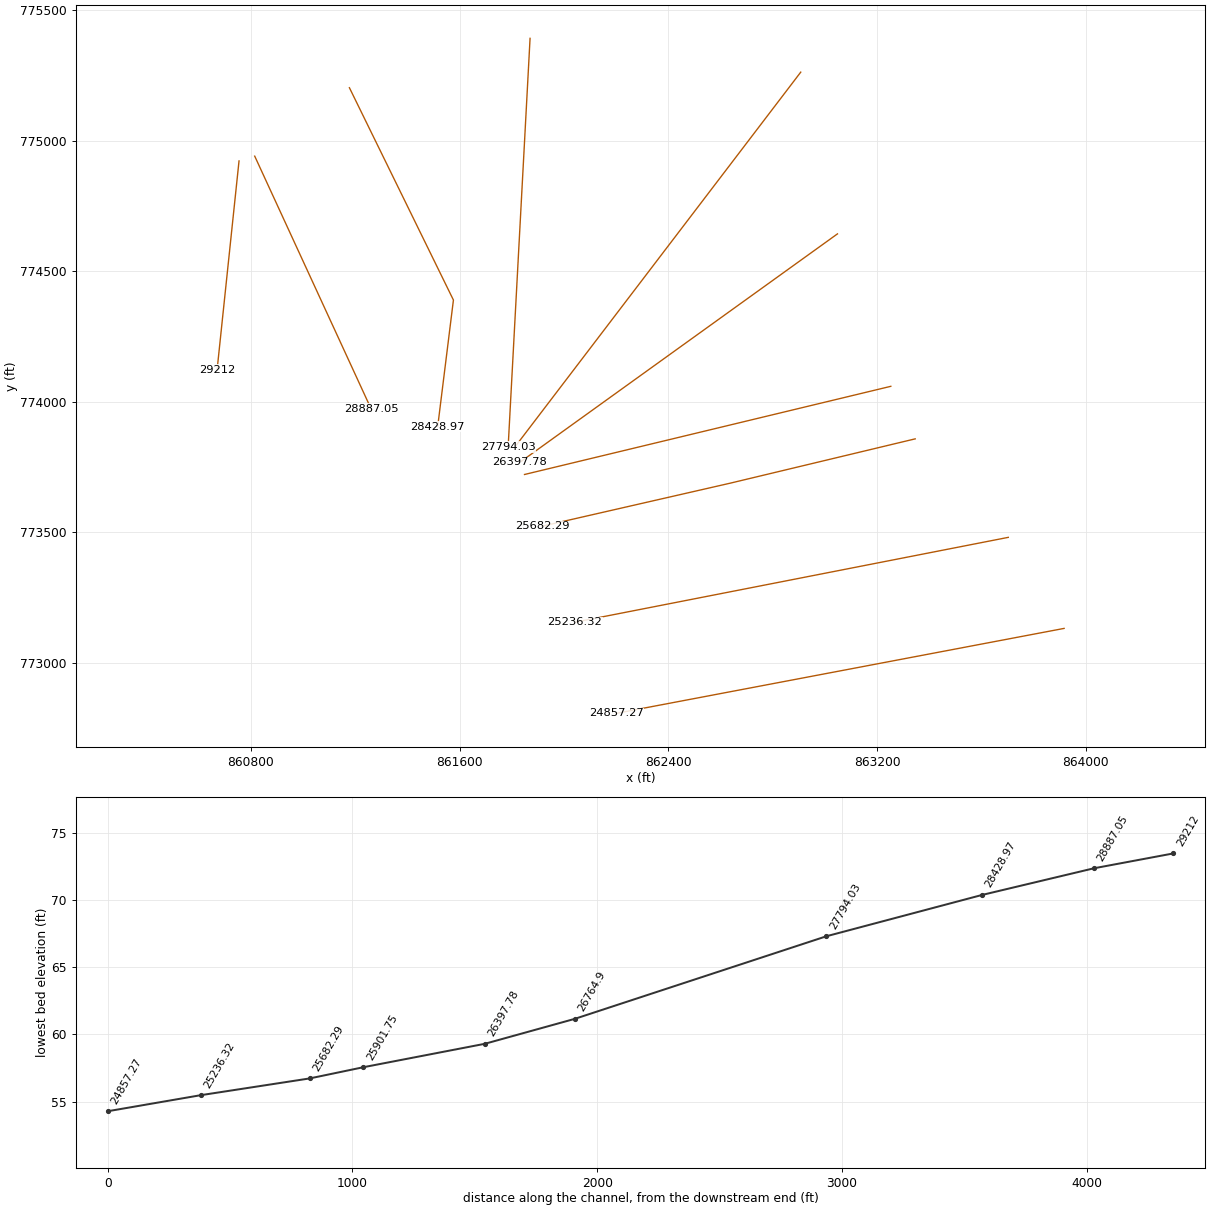
HEC-RAS study 9741_ras.prj: 9741

--- 9741_ras.g01 (geometry) --- (continued)

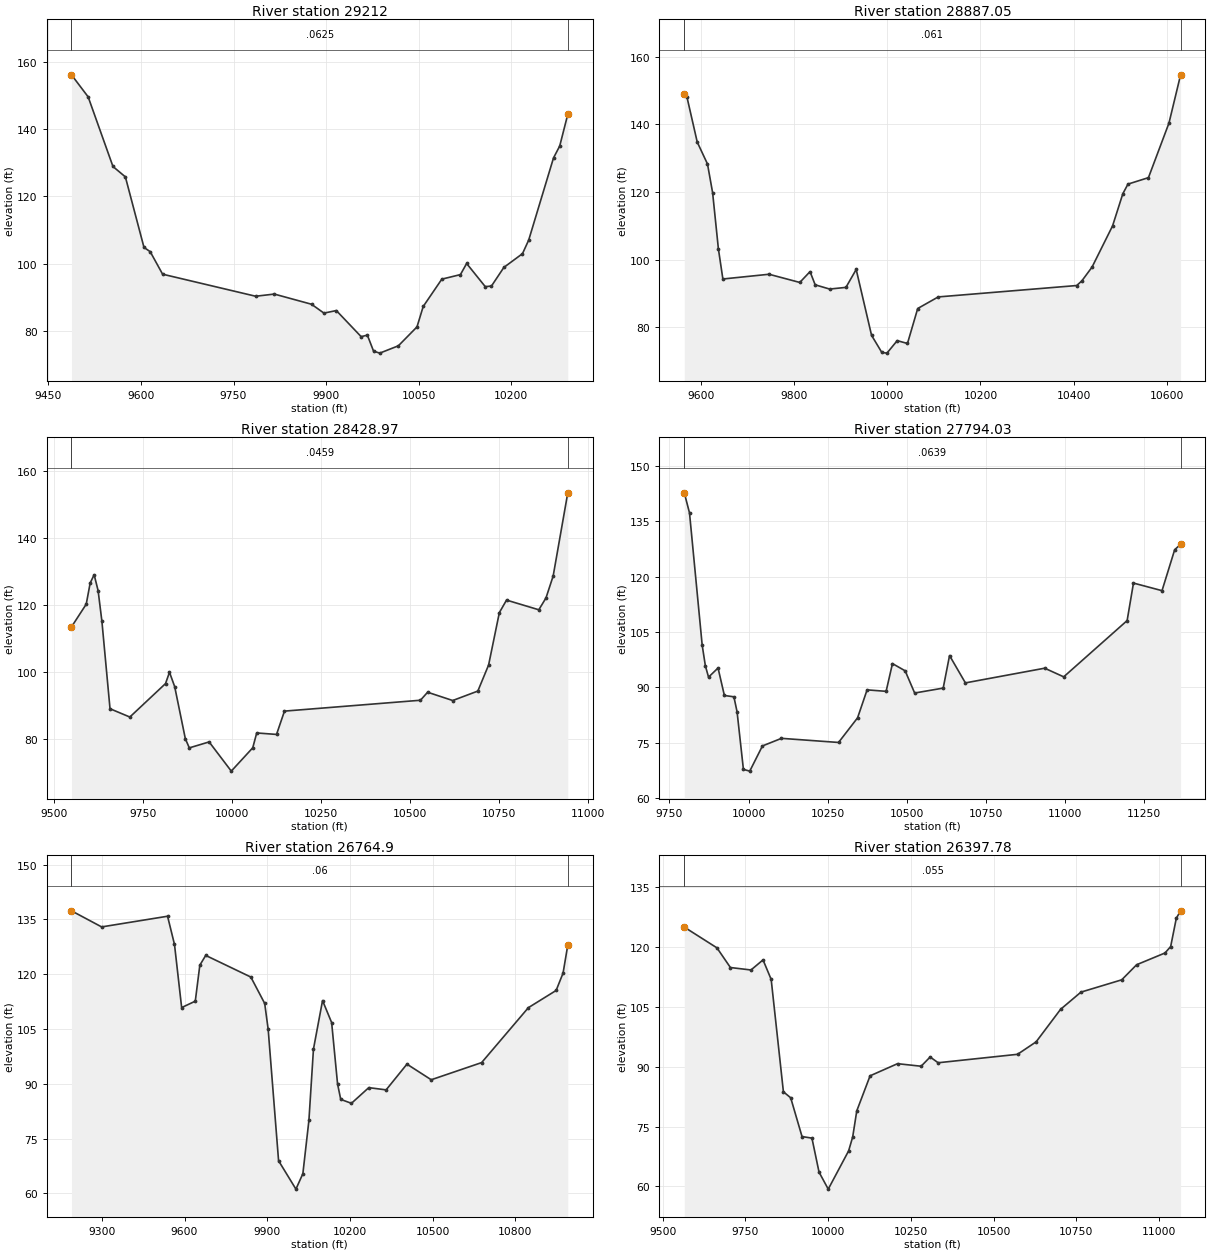
Type RM Length L Ch R = 1 ,   29212,324.948700,324.948700,324.948700
XS GIS Cut Line= 2
860754.213532029774921.862645063860670.152477898774121.991444528
#Sta/Elev= 30
9487.374156.16439514.384 149.6149554.605128.91769574.715125.8271 9604.88104.8622
9614.935103.60379635.04596.906589785.871 90.35329816.03790.999389876.367 87.9752
9896.47785.339189916.587 86.09659956.80878.338539966.86378.798529976.918 74.0285
9986.97373.4459210017.1475.62653 10047.381.2468610057.3687.3120410087.52 95.4343
10117.6996.7857910127.74100.087110157.9193.2082710167.9693.3813310188.0798.92248
10218.24103.007710228.29107.033210268.51131.461710278.57135.004710291.65144.4238
#Mann= 3 , 0 , 0
9487.374  0.0625       09487.374  0.0625       010291.65  0.0625       0
#XS Ineff= 2 , 0
       09695.499        10113.91       0
Bank Sta=9487.374,10291.65
Exp/Cntr=0.3,0.1

Type RM Length L Ch R = 1 ,28887.05,458.076800,458.076800,458.076800
XS GIS Cut Line= 2
  860814.3445719 774940.23845818861260.539768588773972.313358687
#Sta/Elev= 30
9564.101149.11299569.869148.08619591.892134.79039613.914128.30149624.926119.8079
9637.327 103.1899646.94994.276619746.05195.678969812.11993.254719834.14296.46007
9845.153  92.5569876.19591.298369911.22191.793839933.24497.097169966.27877.59419
9988.30172.539269999.31272.3399210021.3476.0330210043.3675.1976310065.3885.54589
10109.4388.9710710406.7392.3420410417.7493.7004710439.7797.8026610483.81109.9878
10505.84119.501810516.85122.350910560.89124.266810604.94140.416910629.92154.6933
#Mann= 3 , 0 , 0
9564.101   0.061       09564.101   0.061       010629.92   0.061       0
#XS Ineff= 2 , 0
       09744.218        10199.48       0
Bank Sta=9564.101,10629.92
Exp/Cntr=0.3,0.1

Type RM Length L Ch R = 1 ,28428.97,634.943600,634.943600,634.943600
XS GIS Cut Line= 3
 861177.36361135775202.198816143861576.031609446774389.126631846
861515.715780706773904.247846161
#Sta/Elev= 30
9548.742113.44289590.172 120.2329601.309126.58179612.446129.02629623.584124.2551
9634.231115.09479656.99688.996339712.68386.51529 9812.9296.510849824.05799.89522
 9838.6695.595849868.60780.025849879.74477.301119935.431 79.08169997.66170.35385
10057.9477.3225810069.0881.7608410124.7781.3174510147.0488.2847110528.9991.53209
10549.1493.9245510619.6891.4515110690.2294.2715410720.46102.053910750.69117.7152
10770.84121.456110861.53118.560410881.69122.103710901.84128.651210942.91153.5034
#Mann= 3 , 0 , 0
9548.742  0.0459       09548.742  0.0459       010942.91  0.0459       0
#XS Ineff= 2 , 0
       0                 10527.5       0
Bank Sta=9548.742,10942.91
Exp/Cntr=0.3,0.1

Type RM Length L Ch R = 1 ,27794.03,1029.126300,1029.126300,1029.126300
XS GIS Cut Line= 2
861869.822548648775391.417145259  861785.7758655773826.390078291
#Sta/Elev= 30
9797.108 142.7059813.549137.26599853.606101.41699863.62195.842639873.63592.76111
9903.678 95.23549923.70787.786539953.75187.426889963.76583.372619983.79467.75585
10003.8267.2887910043.8874.1148110103.9776.1721810284.2375.0571110344.3181.73118
10374.3689.3123610434.4488.9128710454.4796.4313810494.5394.4706310524.5788.45419
 10614.789.7890710634.7398.60251 10684.891.1993610935.1695.1815410995.2592.83852
11195.54108.085711215.57118.2494 11305.7116.191211345.75127.298511364.39128.7381
#Mann= 3 , 0 , 0
9797.108  0.0639       09797.108  0.0639       011364.39  0.0639       0
#XS Ineff= 2 , 0
       0                10820.73       0
Bank Sta=9797.108,11364.39
Exp/Cntr=0.3,0.1

Type RM Length L Ch R = 1 , 26764.9,367.127100,367.127100,367.127100
XS GIS Cut Line= 2
 862907.37230457775261.928012382861815.463333257773831.406785205
#Sta/Elev= 30
9190.139137.35399299.496132.9478 9538.52135.87369563.681128.14119589.604110.8627
9639.048112.6142 9655.53122.46659676.903125.14449840.445119.22019890.766111.9942
9903.347104.91059941.08768.9131910003.9961.1445510029.1565.3646810051.0979.96522
10067.5799.4890610100.53112.780910133.49 106.75910154.95 89.945910166.4685.72122
10205.2784.6432510268.1788.9361310331.0788.3243110406.5695.3715410494.6291.09329
10677.3895.7955310846.86 110.836 10947.5115.546810972.66120.300510989.77127.9657
#Mann= 3 , 0 , 0
9190.139    0.06       09190.139    0.06       010989.77    0.06       0
#XS Ineff= 2 , 0
       0                10112.58       0
Bank Sta=9190.139,10989.77
Exp/Cntr=0.3,0.1

Type RM Length L Ch R = 1 ,26397.78,496.027400,496.027400,496.027400
XS GIS Cut Line= 2
863048.148458861774642.587263098861830.521980397773767.486719963
#Sta/Elev= 30
 9565.31125.02229663.985119.81619704.649114.88449766.794114.26799803.167116.7983
9827.796111.9062 9864.7483.710029886.73882.208149921.00872.478789950.94372.08898
9972.41263.55444 10000.259.2931910061.7868.8889410074.09 72.396310086.4178.92397
10126.6387.7190710209.5590.7639110280.8490.1224610308.07 92.440410332.2490.99604
10572.13 93.113110628.2596.2385610702.14104.397210763.71108.712610886.86111.7983
10931.96115.583711017.64118.532911034.77120.148711051.91127.273311064.78129.1081
#Mann= 3 , 0 , 0
 9565.31   0.055       0 9565.31   0.055       011064.78   0.055       0
#XS Ineff= 2 , 0
       0                10188.17       0
Bank Sta=9565.31,11064.78
Exp/Cntr=0.3,0.1

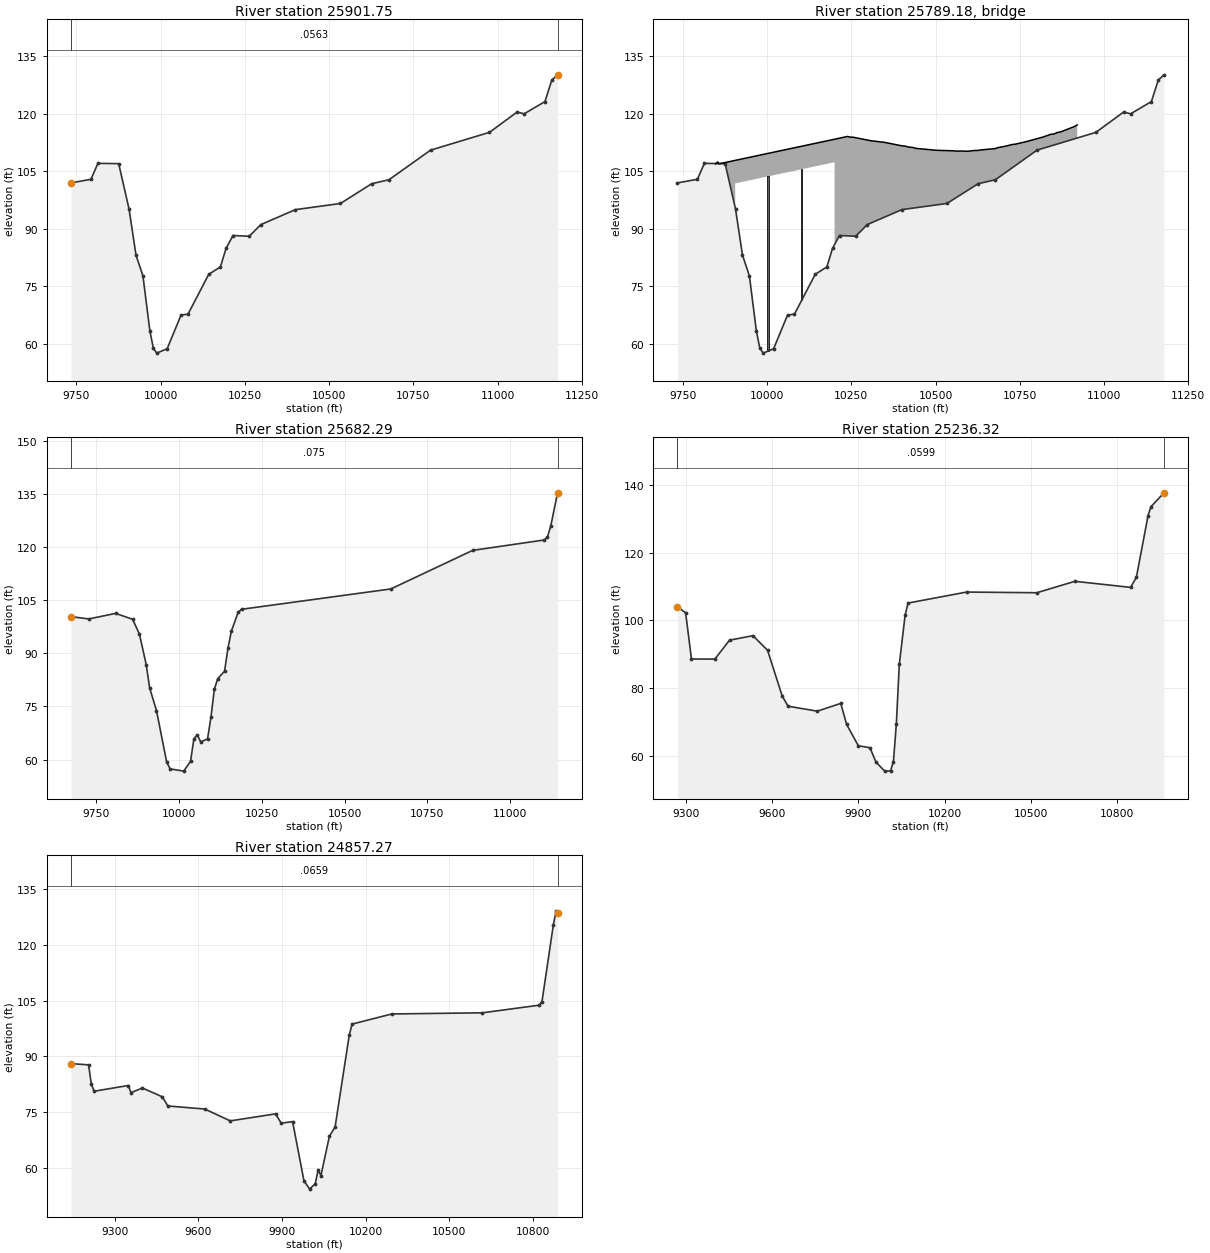
Type RM Length L Ch R = 1 ,25901.75,219.455500,219.455500,219.455500
XS GIS Cut Line= 2
863252.601796516774058.715254533861848.549543972773721.027536953
#Sta/Elev= 30
9733.849101.96329793.094102.89419813.664107.05399875.375106.9811 9906.2395.11439
9926.801 83.12479947.371  77.6919967.94163.399419978.22758.827699988.51257.55342
10019.3758.7173810060.5167.4731810081.0867.7180810142.7978.1228510177.3880.04367
10194.2184.9141210214.7988.2340410262.9188.0392510297.0791.0681410399.9294.98392
10533.6396.5883110626.19  101.7410677.62102.778410801.04110.499110975.89115.1433
11058.17120.453511078.74119.972211140.45 123.16711161.02128.792711177.94130.1492
#Mann= 3 , 0 , 0
9733.849  0.0563       09733.849  0.0563       011177.94  0.0563       0
#XS Ineff= 2 , 0
       0                10234.43       0
Bank Sta=9733.849,11177.94
Exp/Cntr=0.3,0.1

Type RM Length L Ch R = 3 ,25789.18,,,
BEGIN DESCRIPTION:
END DESCRIPTION:
Bridge Culvert--1,0,-1,-1, 0
Deck Dist Width WeirC Skew NumUp NumDn MinLoCord MaxHiCord MaxSubmerge Is_Ogee
34.727750,150.000000,2.6,0, 38, 38, , , 0.95, 0, 0,0,,
 9847.35 9853.56 9856.25 9905.19 9905.1910200.1910200.1910238.7810245.2610255.57
10307.1110348.3410399.8810410.1910420.5010430.7510440.9910502.4510553.6710563.91
10574.1510594.6410615.1310625.3710635.6110676.5910686.8310707.3210727.8010738.05
10768.7810819.9910840.4610850.7210860.9710871.2110912.1810920.33
  106.90  107.45  106.91  107.83  107.83  113.35  113.35  114.08  113.91  113.87
  112.97  112.53  111.63  111.55  111.28  111.23  110.97  110.46  110.33  110.23
  110.28  110.21  110.41  110.42  110.57  110.91  111.19  111.53  111.98  112.08
  112.72  113.95  114.60  114.71  115.09  115.26  116.67  117.09
 -893.10 -892.55 -893.09 -892.17  101.83  107.35 -886.65 -885.92 -886.09 -886.13
 -887.03 -887.47 -888.37 -888.45 -888.72 -888.77 -889.03 -889.54 -889.67 -889.77
 -889.72 -889.79 -889.59 -889.58 -889.43 -889.09 -888.81 -888.47 -888.02 -887.92
 -887.28 -886.05 -885.40 -885.29 -884.91 -884.74 -883.33 -882.91
 9847.35 9853.56 9856.25 9884.86 9884.8610179.8610179.8610238.7810245.2610255.57
10307.1110348.3410399.8810410.1910420.5010430.7510440.9910502.4510553.6710563.91
10574.1510594.6410615.1310625.3710635.6110676.5910686.8310707.3210727.8010738.05
10768.7810819.9910840.4610850.7210860.9710871.2110912.1810920.33
  106.90  107.45  106.91  107.45  107.45  112.97  112.97  114.08  113.91  113.87
  112.97  112.53  111.63  111.55  111.28  111.23  110.97  110.46  110.33  110.23
  110.28  110.21  110.41  110.42  110.57  110.91  111.19  111.53  111.98  112.08
  112.72  113.95  114.60  114.71  115.09  115.26  116.67  117.09
 -893.10 -892.55 -893.09 -892.55  101.45  106.97 -887.03 -885.92 -886.09 -886.13
 -887.03 -887.47 -888.37 -888.45 -888.72 -888.77 -889.03 -889.54 -889.67 -889.77
 -889.72 -889.79 -889.59 -889.58 -889.43 -889.09 -888.81 -888.47 -888.02 -887.92
 -887.28 -886.05 -885.40 -885.29 -884.91 -884.74 -883.33 -882.91
Pier Skew, UpSta & Num, DnSta & Num=  ,10002.86, 2 ,9982.52, 2 , 0 , 0 , 0 ,,
    4.00    4.00
 -890.34  109.66
    4.00    4.00
 -890.72  109.28
Pier Skew, UpSta & Num, DnSta & Num=  ,10102.53, 2 ,10082.19, 2 , 0 , 0 , 0 ,,
    4.00    4.00
 -888.47  111.53
    4.00    4.00
 -888.85  111.15
BR Coef=-1 , 0 , 0 ,, 0 ,,,0.8,0,1,0,
WSPro=,,,, 1 ,,,, 0 ,,,, 0 ,,,,-1 ,-1 ,-1 , 0 , 0 , 0 , 0 , 0
BC Design=,, 0 ,, 0 ,,,,,,

Type RM Length L Ch R = 1 ,25682.29,445.974600,445.974600,445.974600
XS GIS Cut Line= 3
863346.081251261773857.518649835862637.456629515773687.910041968
861915.199533706773522.775424955
#Sta/Elev= 30
9673.476100.30849727.25699.67057 9808.26 101.2329859.67299.573989880.23795.36339
9900.802 86.72029911.08480.167039931.64973.821369962.49759.277869972.77957.34687
10013.9156.7202210034.4759.4768310044.7665.8559310055.0466.9289810065.3264.95968
10085.8965.8280810096.1771.8837910106.4579.8134410116.7382.82851 10137.384.92624
10147.5891.3938710157.8696.2371510178.43101.544610188.71102.3929 10639.5108.1314
10886.76119.020811102.18121.939711112.44122.7408 11122.7125.962611143.01135.2578
#Mann= 3 , 0 , 0
9673.476   0.075       09673.476   0.075       011143.01   0.075       0
#XS Ineff= 2 , 0
       0                10212.24       0
Bank Sta=9673.476,11143.01
Exp/Cntr=0.3,0.1

Type RM Length L Ch R = 1 ,25236.32,379.050600,379.050600,379.050600
XS GIS Cut Line= 2
863702.895558339773480.287053126862040.532631369773155.035301382
#Sta/Elev= 30
9269.974103.98079298.398102.24199318.77888.582919400.294 88.56799451.24294.15315
9532.75995.483139583.70791.154469634.65577.647179655.03574.648999756.93173.17867
9838.448 75.47999858.82769.289599899.58562.969149940.34462.379069960.72358.19297
9991.29255.4723710011.6755.5245410021.8658.2869210032.0569.4571410042.2486.96532
10062.62101.592810072.81105.1118 10276.6108.362410521.15108.160410653.62111.5364
10847.22109.7432 10867.6112.684510908.36130.959210918.55 133.59310963.86137.6694
#Mann= 3 , 0 , 0
9269.974  0.0599       09269.974  0.0599       010963.86  0.0599       0
#XS Ineff= 2 , 0
       09551.409                       0
Bank Sta=9269.974,10963.86
Exp/Cntr=0.3,0.1

Type RM Length L Ch R = 1 ,24857.27,841.335700,841.335700,841.335700
XS GIS Cut Line= 2
863916.912741832773131.615402965862200.084685869772806.179796694
#Sta/Elev= 30
9142.26288.029779205.27887.695749215.45682.428339225.63480.608489347.771 82.1427
9357.949  80.2219398.66181.478979469.90879.113779490.26476.640489622.57975.81989
9714.18172.63371 9877.0374.518129897.38772.003819938.09972.442819978.81156.56685
9999.167 54.281810019.5255.73531 10029.759.3807810039.8857.9325410070.4168.52814
10090.7770.9993110141.6695.7003310151.8498.6567610294.33101.379610620.03101.6908
10823.59103.739210833.77104.713910874.48125.277510884.66 129.11210889.66128.4515
#Mann= 3 , 0 , 0
9142.262  0.0659       09142.262  0.0659       010889.66  0.0659       0
#XS Ineff= 2 , 0
       09648.706                       0
Bank Sta=9142.262,10889.66
Exp/Cntr=0.3,0.1