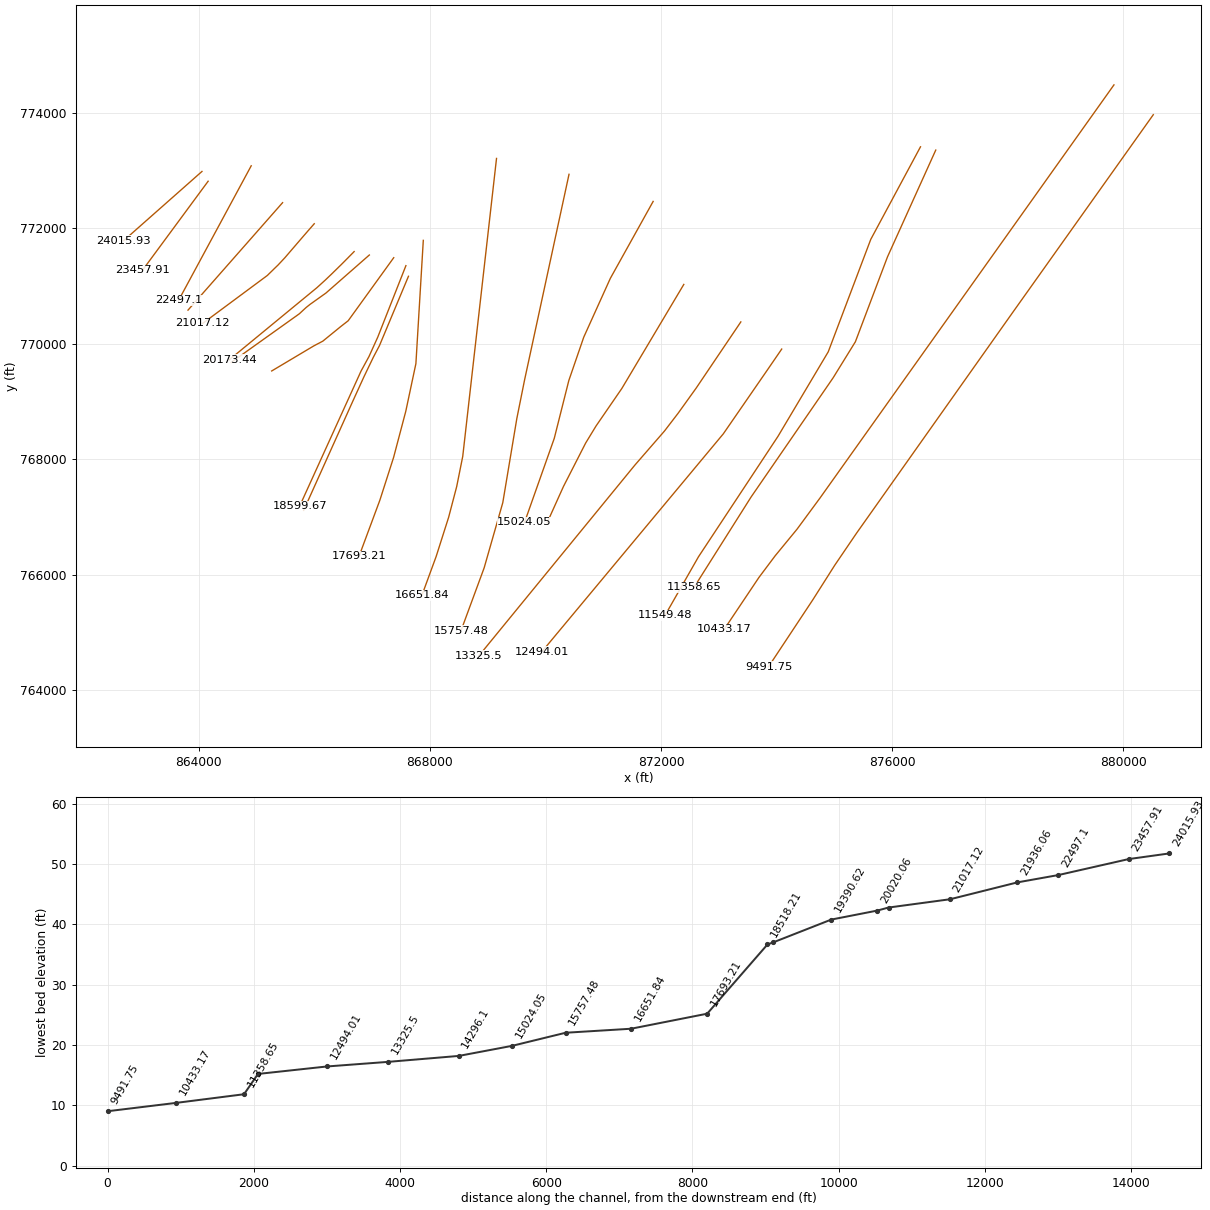
HEC-RAS study 9741_ras.prj: 9741

--- 9741_ras.g01 (geometry) --- (continued)

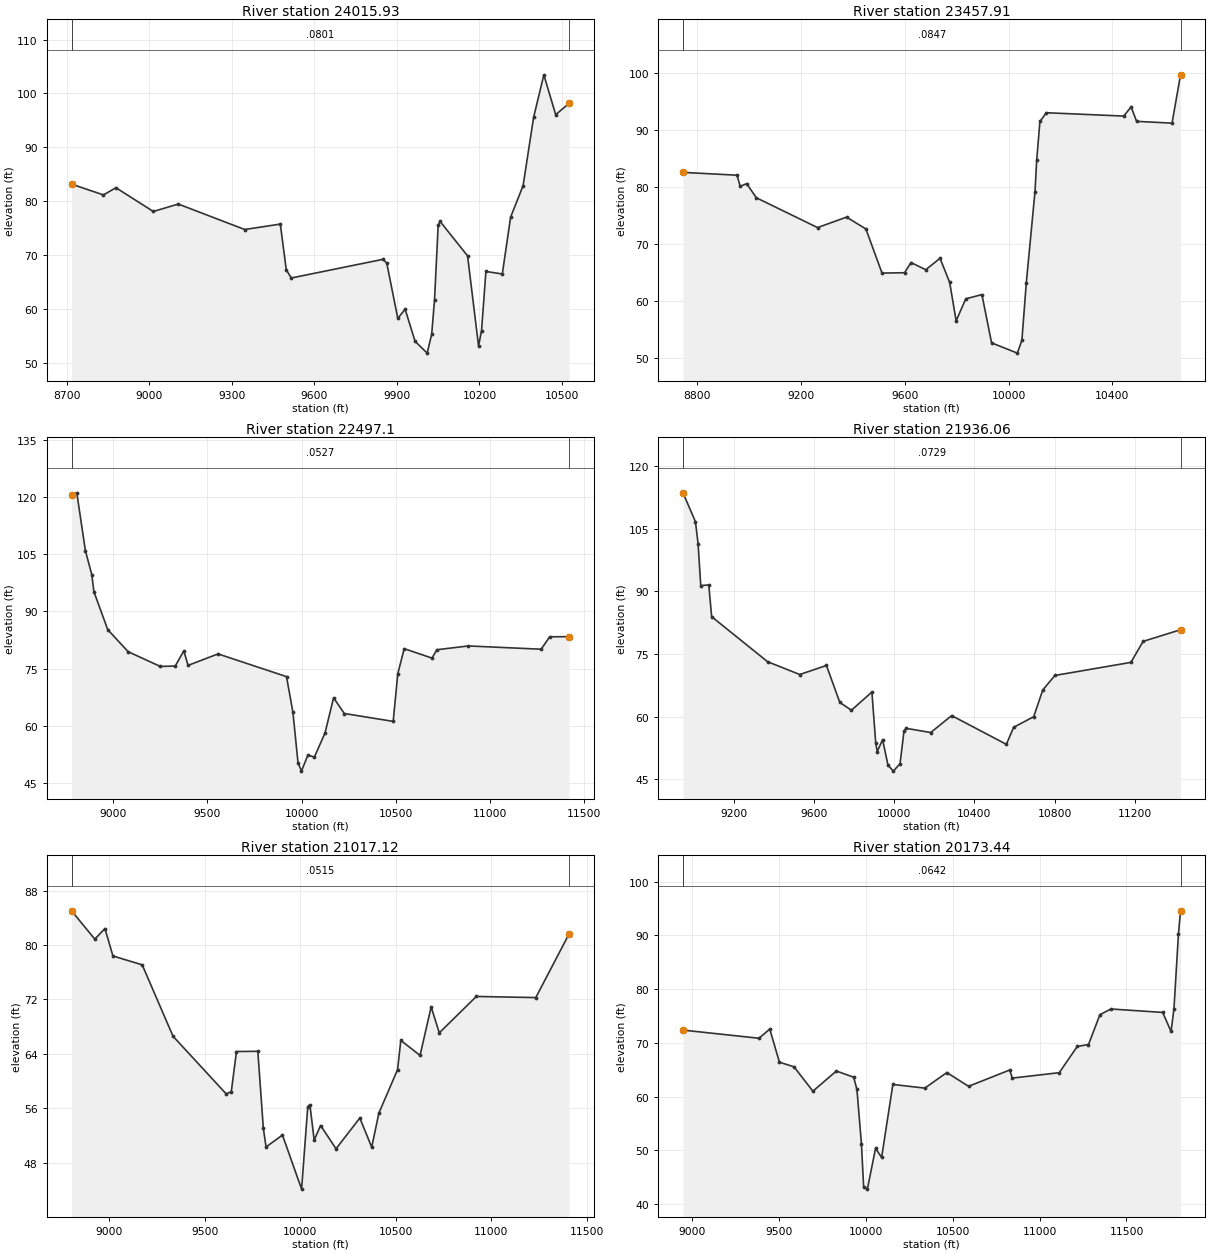
Type RM Length L Ch R = 1 ,24015.93,558.025100,558.025100,558.025100
XS GIS Cut Line= 2
864053.650988904772981.844668118862698.474293715771784.272533348
#Sta/Elev= 30
8717.14183.137658833.18781.131388878.49182.470389014.40478.053139105.01279.43955
9346.635  74.7089476.01475.715399497.64967.212569516.04965.700879849.67869.17657
9863.02368.433579903.05858.210369929.74959.898359965.793 53.946910009.8251.74611
 10026.255.2478110036.5161.6079510049.8575.51093 10056.476.2274910156.6269.81957
10196.6553.0556410207.4255.9410610223.3466.9118510282.9266.4526510313.1377.00824
10358.4382.8443710396.8395.5738210433.94103.4394 10476.996.0388910525.6498.13741
#Mann= 3 , 0 , 0
8717.141  0.0801       08717.141  0.0801       010525.64  0.0801       0
#XS Ineff= 2 , 0
       09446.386        10075.18       0
Bank Sta=8717.141,10525.64
Exp/Cntr=0.3,0.1

Type RM Length L Ch R = 1 ,23457.91,960.802200,960.802200,960.802200
XS GIS Cut Line= 2
864160.539542875772812.563961443863021.952550654771268.635040679
#Sta/Elev= 30
8744.37282.549758952.57382.056998964.99880.092478989.84880.574219027.12478.09229
9263.202 72.85499375.02974.69391 9449.5872.613599511.706 64.86319598.682 64.9278
9623.53266.711339680.37765.453129735.35967.459419772.63463.225979797.48456.48388
 9834.76 60.34659896.88661.085579934.16152.6100210033.5650.8058810051.0553.06312
10067.8963.0949310101.5979.1871210108.1184.7275510120.5491.4868910145.3993.02619
10443.5992.4403610472.2694.0543110493.2991.5129410629.97 91.198310662.7399.68406
#Mann= 3 , 0 , 0
8744.372  0.0847       08744.372  0.0847       010662.73  0.0847       0
#XS Ineff= 2 , 0
       0 9335.94                       0
Bank Sta=8744.372,10662.73
Exp/Cntr=0.3,0.1

Type RM Length L Ch R = 1 , 22497.1,561.044700,561.044700,561.044700
XS GIS Cut Line= 2
864906.209150231773079.591795399863651.375463743770754.496718855
#Sta/Elev= 30
8778.568120.57858806.512121.06968851.966105.94238886.05699.644478897.41995.16698
8970.61285.234569079.23479.442989249.68575.591959329.22875.686949374.68279.64844
9397.40975.860189556.49678.869899920.12572.915949954.21563.573849981.26950.32893
9999.66848.1601310033.7652.3981910067.85 51.814410124.6758.1640310170.1267.37265
10226.9463.25596 10486.661.1937610511.0273.6703710545.1180.2421110692.8477.76945
10718.21 79.960610886.01 80.957211272.3780.0963911317.8283.3626211420.6683.37812
#Mann= 3 , 0 , 0
8778.568  0.0527       08778.568  0.0527       011420.66  0.0527       0
#XS Ineff= 2 , 0
       0                               0
Bank Sta=8778.568,11420.66
Exp/Cntr=0.3,0.1

Type RM Length L Ch R = 1 ,21936.06,918.944500,918.944500,918.944500
XS GIS Cut Line= 2
 865449.30902883772441.405700523863811.745206076770580.874581336
#Sta/Elev= 30
8948.233113.61419010.053106.72259023.375101.44839036.69691.403269076.66191.53827
9090.97583.943919369.73973.148619529.90670.089619662.81772.256769729.42563.40648
9787.21161.527619889.28665.893579908.29553.688729915.92951.642789942.57354.48646
9969.21648.41351 9995.8646.9427310029.3848.7089110049.1556.5306410059.6557.20114
10182.3656.1908610286.6860.2441510559.1253.3631910595.34 57.435810695.3559.98396
10740.7566.4153610801.29 69.866811179.6872.9955311240.2378.0233811426.7880.81641
#Mann= 3 , 0 , 0
8948.233  0.0729       08948.233  0.0729       011426.78  0.0729       0
#XS Ineff= 2 , 0
       0                               0
Bank Sta=8948.233,11426.78
Exp/Cntr=0.3,0.1

Type RM Length L Ch R = 1 ,21017.12,843.674200,843.674200,843.674200
XS GIS Cut Line= 6
865997.526916259772076.662943648865839.930450257771896.120910458
865487.680678833771486.627864208 865374.73745709771366.009850103
865184.438156171771180.188224598864064.993228252770350.418482103
#Sta/Elev= 30
  8803.185.021198924.77380.869058977.86982.411899019.83578.391289172.98677.08807
9334.42566.598499612.19858.152149639.28858.447769666.378 64.35759778.26864.38972
9806.92953.13516 9821.2650.343979907.24352.08887 10007.444.1506810039.6556.27853
10050.7956.5428910073.24 51.347810106.8253.4938810187.7150.0802710312.1954.59482
10374.4250.3062210411.7755.3095910509.8661.7068710526.6565.9947210627.4163.78861
10685.6170.9098910728.1767.1021810922.1272.4457911233.3172.2803711407.5881.63206
#Mann= 3 , 0 , 0
  8803.1  0.0515       0  8803.1  0.0515       011407.58  0.0515       0
#XS Ineff= 2 , 0
       0                               0
Bank Sta=8803.1,11407.58
Exp/Cntr=0.3,0.1

Type RM Length L Ch R = 1 ,20173.44,153.384300,153.384300,153.384300
XS GIS Cut Line= 6
866688.394928317771594.577917689866486.956868599771390.715448385
 866309.67522786771216.926499325866188.320928915771101.069114577
866046.100090585770971.535200194864525.689347673769720.331180384
#Sta/Elev= 30
8947.08972.379749384.699 70.86069446.47872.574139502.23166.404059586.102 65.5447
9694.791 61.00689830.05164.760949929.24863.610499948.379 61.32699974.16351.23113
9987.05543.1935410008.3342.7707410055.67 50.368310090.4748.6729910155.1962.25821
10339.1461.5796410465.85 64.473710591.1261.9145110827.3664.9456210843.1163.44818
11113.0664.4522411216.6169.3393911281.3469.6946511347.08  75.24911410.7876.31347
11708.4975.6704711756.5672.1224911773.2276.32267 11799.190.2635911811.1694.58771
#Mann= 3 , 0 , 0
8947.089  0.0642       08947.089  0.0642       011811.16  0.0642       0
#XS Ineff= 2 , 0
       09544.156                       0
Bank Sta=8947.089,11811.16
Exp/Cntr=0.3,0.1

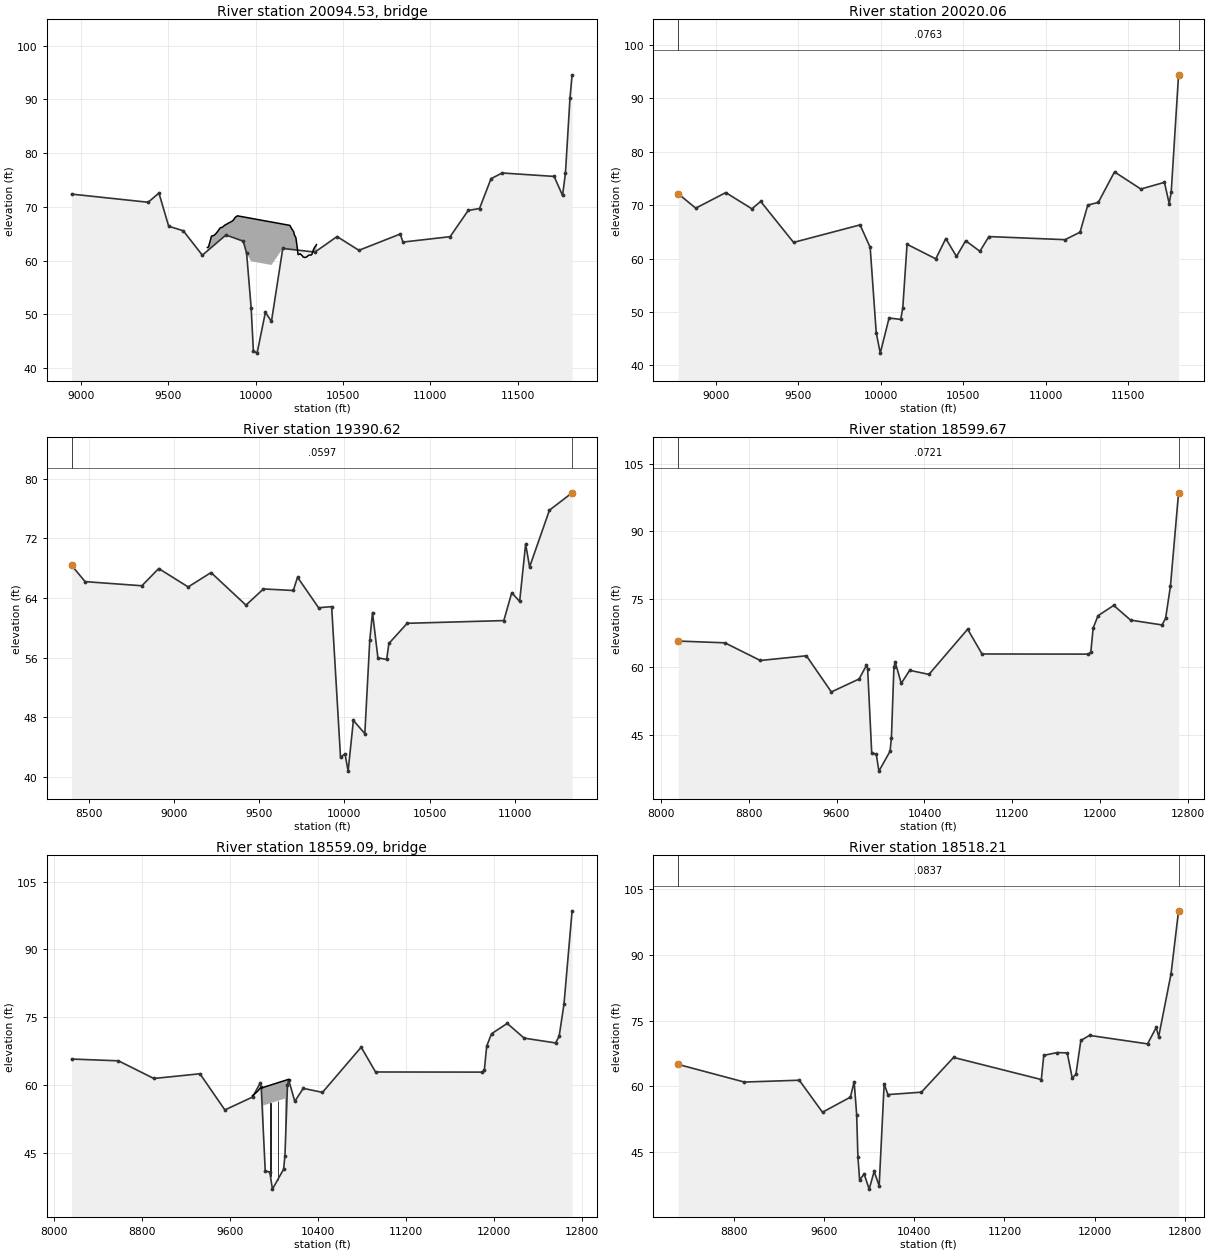
Type RM Length L Ch R = 3 ,20094.53,,,
BEGIN DESCRIPTION:
END DESCRIPTION:
Bridge Culvert--1,0,-1,-1, 0
Deck Dist Width WeirC Skew NumUp NumDn MinLoCord MaxHiCord MaxSubmerge Is_Ogee
48.192150,57.000000,2.6,0, 53, 53, , , 0.95, 0, 0,0,,
 9723.77 9730.30 9734.74 9747.12 9747.26 9759.50 9764.22 9771.88 9781.18 9784.26
 9796.65 9798.14 9809.03 9815.11 9821.41 9832.07 9833.79 9846.17 9849.03 9858.55
 9865.99 9870.93 9882.95 9883.31 9895.69 9896.27 9918.27 9918.2710173.2710173.27
10195.6710204.8910205.3910217.8810221.5810230.3710238.2610242.8610254.9510255.35
10267.8410271.6410280.3410288.3210292.8310305.0110305.3210317.8110321.7010330.30
10338.3810342.8010348.15
   62.46   62.53   63.07   64.55   64.56   64.67   64.75   65.00   65.36   65.51
   66.07   66.11   66.21   66.35   66.55   66.76   66.76   67.02   67.06   67.21
   67.37   67.48   68.04   68.05   68.34   68.33   68.20   68.20   66.69   66.69
   66.56   66.01   65.97   65.36   64.79   64.26   62.36   61.11   61.27   61.25
   60.87   60.68   60.59   60.62   60.72   61.03   61.03   61.03   61.15   62.00
   62.54   62.65   62.98
 -937.54 -937.47 -936.93 -935.45 -935.44 -935.33 -935.25 -935.00 -934.64 -934.49
 -933.93 -933.89 -933.79 -933.65 -933.45 -933.24 -933.24 -932.98 -932.94 -932.79
 -932.63 -932.52 -931.96 -931.95 -931.66 -931.67 -931.80   60.20   58.69 -933.31
 -933.44 -933.99 -934.03 -934.64 -935.21 -935.74 -937.64 -938.89 -938.73 -938.75
 -939.13 -939.32 -939.41 -939.38 -939.28 -938.97 -938.97 -938.97 -938.85 -938.00
 -937.46 -937.35 -937.02
 9723.77 9730.30 9734.74 9747.12 9747.26 9759.50 9764.22 9771.88 9781.18 9784.26
 9796.65 9798.14 9809.03 9815.11 9821.41 9832.07 9833.79 9846.17 9849.03 9858.55
 9865.99 9870.93 9882.95 9883.31 9895.69 9896.27 9917.99 9917.9910172.9910172.99
10195.6710204.8910205.3910217.8810221.5810230.3710238.2610242.8610254.9510255.35
10267.8410271.6410280.3410288.3210292.8310305.0110305.3210317.8110321.7010330.30
10338.3810342.8010348.15
   62.46   62.53   63.07   64.55   64.56   64.67   64.75   65.00   65.36   65.51
   66.07   66.11   66.21   66.35   66.55   66.76   66.76   67.02   67.06   67.21
   67.37   67.48   68.04   68.05   68.34   68.33   68.20   68.20   66.69   66.69
   66.56   66.01   65.97   65.36   64.79   64.26   62.36   61.11   61.27   61.25
   60.87   60.68   60.59   60.62   60.72   61.03   61.03   61.03   61.15   62.00
   62.54   62.65   62.98
 -937.54 -937.47 -936.93 -935.45 -935.44 -935.33 -935.25 -935.00 -934.64 -934.49
 -933.93 -933.89 -933.79 -933.65 -933.45 -933.24 -933.24 -932.98 -932.94 -932.79
 -932.63 -932.52 -931.96 -931.95 -931.66 -931.67 -931.80   60.20   58.69 -933.31
 -933.44 -933.99 -934.03 -934.64 -935.21 -935.74 -937.64 -938.89 -938.73 -938.75
 -939.13 -939.32 -939.41 -939.38 -939.28 -938.97 -938.97 -938.97 -938.85 -938.00
 -937.46 -937.35 -937.02
BR Coef=-1 , 0 , 0 ,, 0 ,,,0.8,0,1,0,
WSPro=,,,, 1 ,,,, 0 ,,,, 0 ,,,,-1 ,-1 ,-1 , 0 , 0 , 0 , 0 , 0
BC Design=,, 0 ,, 0 ,,,,,,

Type RM Length L Ch R = 1 ,20020.06,629.432300,629.432300,629.432300
XS GIS Cut Line= 6
866951.201851619771535.300175695 866200.86777904770877.397142446
865924.404723071770680.346318314865854.809954168770624.543322994
865738.875571221770517.204625681864558.843107681769675.330769298
#Sta/Elev= 30
 8772.18 72.14658878.81369.43202 9060.8372.354729219.31669.312589272.515 70.6951
9472.00963.019759875.24766.298689936.47562.093479973.21146.099729997.67942.26884
10051.14 48.844110121.6648.5882810134.1450.6950610160.1262.66305 10334.359.93901
10395.0863.7358810459.8860.3831710515.6163.33209 10601.761.3568310656.4364.11227
11118.2563.5294811209.2164.9362611255.9970.0178911319.77 70.512711418.04 76.2318
11577.7373.0182411720.8974.2733711749.7170.2702111761.9972.5176511806.4194.42101
#Mann= 3 , 0 , 0
 8772.18  0.0763       0 8772.18  0.0763       011806.41  0.0763       0
#XS Ineff= 2 , 0
       09355.076                       0
Bank Sta=8772.18,11806.41
Exp/Cntr=0.3,0.1

Type RM Length L Ch R = 1 ,19390.62,790.951300,790.951300,790.951300
XS GIS Cut Line= 6
867373.575547919771488.876561729866585.061076347770397.103293017
866460.195138306770299.797309013866144.970553655770043.199548374
865992.167313488769963.073577644865260.863532904769527.617183415
#Sta/Elev= 30
8400.89768.375458479.69166.203078812.74765.64955 8911.4367.962259084.12665.48952
9218.28167.418599423.23663.047419525.71365.222549700.89565.013169725.56666.79279
9849.14362.69801 9925.7462.847969977.84642.6232810004.0543.10574 10022.340.77734
10053.28 47.576810120.3845.8044310149.3858.35291 10165.462.0486710197.1855.97279
10248.3955.76106 10261.5 57.906510368.8660.6114610935.5860.9766710982.1364.71186
11028.4963.54697 11063.671.2492311086.8868.1707411203.2775.7924211336.1178.11776
#Mann= 3 , 0 , 0
8400.897  0.0597       08400.897  0.0597       011336.11  0.0597       0
#XS Ineff= 2 , 0
       09750.918        11265.32       0
Bank Sta=8400.897,11336.11
Exp/Cntr=0.3,0.1

Type RM Length L Ch R = 1 ,18599.67,81.460600,81.460600,81.460600
XS GIS Cut Line= 5
867584.457423592771350.836612355867096.908027413 770112.87869992
866945.774656937769778.981517428866807.985653359769526.323816738
865744.952688101767187.804585737
#Sta/Elev= 30
8158.69965.770398584.12865.377178906.55561.472319325.71162.515899552.73654.51925
  9805.257.380949871.63860.365579883.02959.694459919.989 41.09619961.76140.72895
9985.54337.0144910087.0841.4123310099.4544.4177110122.2359.9922910133.6261.13809
10188.8956.4104510265.7959.2978310440.6958.3979310793.0568.3919810923.9962.91084
11890.5862.8814411913.4963.2577211935.4668.65927 11979.471.36597 12122.273.65023
12275.9970.3943512561.5969.3324612594.5570.8016812638.4877.91105 12712.398.53477
#Mann= 3 , 0 , 0
8158.699  0.0721       08158.699  0.0721       0 12712.3  0.0721       0
#XS Ineff= 2 , 0
       09651.993        10133.25       0
Bank Sta=8158.699,12712.3
Exp/Cntr=0.3,0.1

Type RM Length L Ch R = 3 ,18559.09,,,
BEGIN DESCRIPTION:
END DESCRIPTION:
Bridge Culvert--1,0,-1,-1, 0
Deck Dist Width WeirC Skew NumUp NumDn MinLoCord MaxHiCord MaxSubmerge Is_Ogee
18.730300,44.000000,2.6,0, 18, 18, , , 0.95, 0, 0,0,,
 9802.08 9810.09 9818.76 9821.30 9832.51 9840.89 9843.72 9854.93 9863.02 9866.14
 9870.59 9902.61 9902.6110099.6110099.6110131.1610135.1810140.24
   57.62   57.81   57.96   58.02   58.25   58.43   58.50   58.76   59.02   59.12
   59.26   59.51   59.51   61.03   61.03   61.28   61.23   61.16
 -942.38 -942.19 -942.04 -941.98 -941.75 -941.57 -941.50 -941.24 -940.98 -940.88
 -940.74 -940.49   55.51   57.03 -938.97 -938.72 -938.77 -938.84
 9802.08 9810.09 9818.76 9821.30 9832.51 9840.89 9843.72 9854.93 9863.02 9866.14
 9870.59 9897.65 9897.6510094.6510094.6510131.1610135.1810140.24
   57.62   57.81   57.96   58.02   58.25   58.43   58.50   58.76   59.02   59.12
   59.26   59.47   59.47   61.00   61.00   61.28   61.23   61.16
 -942.38 -942.19 -942.04 -941.98 -941.75 -941.57 -941.50 -941.24 -940.98 -940.88
 -940.74 -940.53   55.47   57.00 -939.00 -938.72 -938.77 -938.84
Pier Skew, UpSta & Num, DnSta & Num=  ,9967.61, 2 ,9962.65, 2 , 0 , 0 , 0 ,,
    4.00    4.00
 -939.99   60.01
    4.00    4.00
 -940.03   59.97
Pier Skew, UpSta & Num, DnSta & Num=  ,10034.61, 2 ,10029.65, 2 , 0 , 0 , 0 ,,
    4.00    4.00
 -939.47   60.53
    4.00    4.00
 -939.51   60.49
BR Coef=-1 , 0 , 0 ,, 0 ,,,0.8,0,1,0,
WSPro=,,,, 1 ,,,, 0 ,,,, 0 ,,,,-1 ,-1 ,-1 , 0 , 0 , 0 , 0 , 0
BC Design=,, 0 ,, 0 ,,,,,,

Type RM Length L Ch R = 1 ,18518.21,825.004000,825.004000,825.004000
XS GIS Cut Line= 6
867628.570575909771166.813733367867125.865320415769965.345811436
867022.545933271769769.394130554866857.824898118769426.838546399
866667.787364398769010.371337912865814.511247064767114.216135717
#Sta/Elev= 30
8304.29665.024098891.62561.012459379.42761.426169585.38854.146919833.09157.57846
9866.37961.085839888.571 53.58299899.667 44.00779914.85438.749939955.14840.09369
9999.53236.6543610043.9240.67977 10088.337.4071110132.6860.5826210165.9758.15715
10463.1558.7077710748.7466.6148611527.3261.5833911549.2567.0902411669.8867.72225
 11757.667.6352811801.4761.9520411834.3762.7497211878.2370.4652811954.9971.62599
12470.3969.6933912547.15  73.42412569.0871.3459112678.7485.6359412745.3999.95876
#Mann= 3 , 0 , 0
8304.296  0.0837       08304.296  0.0837       012745.39  0.0837       0
#XS Ineff= 2 , 0
       09654.445        10138.14       0
Bank Sta=8304.296,12745.39
Exp/Cntr=0.3,0.1

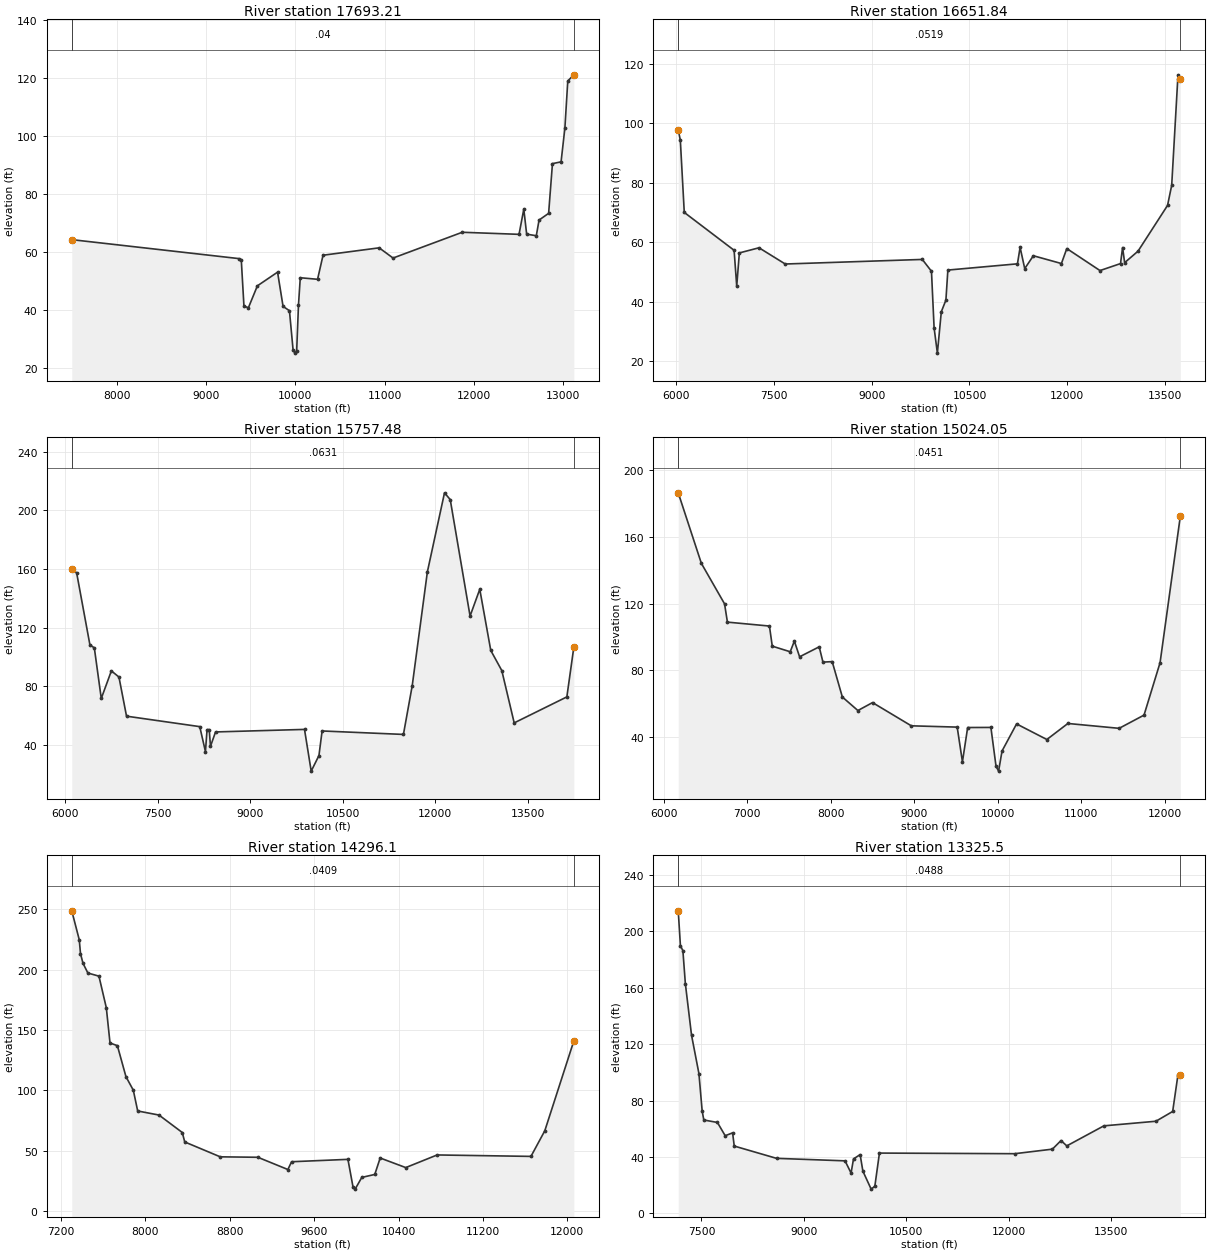
Type RM Length L Ch R = 1 ,17693.21,1041.371100,1041.371100,1041.371100
XS GIS Cut Line= 6
867885.466495115771788.628669135867757.451368437769655.444125103
867582.171258853768829.598880835 867371.19889958768030.721550332
867133.867880677767291.472115349866773.794220127766321.897561663
#Sta/Elev= 30
 7499.1364.245879366.11157.734249396.16557.320769426.21941.323639476.30940.82902
9576.489 48.34129802.344 53.05289863.82541.270739935.305 39.7745 9975.7526.36958
9995.973 25.173410016.1725.9491610036.3841.7424410056.5951.1327510250.0450.59399
10311.3758.88406 10939.461.4280711094.8757.9137311869.2566.7883412504.7766.07459
12558.1174.7392512590.1366.1339612698.0765.5979412728.9170.9924612835.9473.30434
 12878.890.4177812975.26 91.035413018.12102.720513050.32118.887613118.22120.9978
#Mann= 3 , 0 , 0
 7499.13    0.04       0 7499.13    0.04       013118.22    0.04       0
#XS Ineff= 2 , 0
       0 9339.63        10361.08       0
Bank Sta=7499.13,13118.22
Exp/Cntr=0.3,0.1

Type RM Length L Ch R = 1 ,16651.84,894.356400,894.356400,894.356400
XS GIS Cut Line= 6
869153.064437368 773206.97172611868568.278647845768048.848567502
868463.193319649767524.666244701868324.246320207766994.986471255
868107.610895424766314.705774268867860.663618133 765641.82046957
#Sta/Elev= 30
 6030.7597.827146062.92194.286826123.29570.003226888.033 57.26416928.28245.21171
6968.53256.379747270.402 58.10887672.89552.651099775.92454.190519916.79750.20769
9957.04631.1905310007.36 22.680110067.7336.5988810138.1740.5012610168.3650.61408
11236.1452.7132311276.7458.2556911347.8151.1092711480.1855.4291611910.7952.81138
11993.42 57.847512502.7350.4466912817.71 52.795512849.3658.1968712881.0153.09797
13086.2656.96869 13539.272.34876 13603.279.1365113699.68116.275413735.26114.9913
#Mann= 3 , 0 , 0
 6030.75  0.0519       0 6030.75  0.0519       013735.26  0.0519       0
#XS Ineff= 2 , 0
       09057.428        11286.15       0
Bank Sta=6030.75,13735.26
Exp/Cntr=0.3,0.1

Type RM Length L Ch R = 1 ,15757.48,733.428000,733.428000,733.428000
XS GIS Cut Line= 6
870408.159326505772932.347562974869639.966558237769378.222878877
869504.926969645768705.732657035869261.654497143767247.653858805
868938.739755215766118.269171301868537.450760755765029.544207506
#Sta/Elev= 30
6109.898160.20566189.031157.27546403.881108.17476475.497106.10466588.03771.60328
6751.73290.418886874.50386.219386997.27459.51047 8184.0652.376528276.139 35.3538
8302.23650.298598337.52450.309978357.98638.953878439.83348.754569881.63950.47946
9990.04922.0158410115.69  32.65510166.7849.4197811484.7847.0595711627.2580.31135
11872.69157.966412150.38211.906712243.29207.275612564.62 127.82112721.93146.1031
 12900.1104.374313078.8990.6363213279.7254.9281814133.1972.6655814246.44106.6701
#Mann= 3 , 0 , 0
6109.898  0.0631       06109.898  0.0631       014246.44  0.0631       0
#XS Ineff= 2 , 0
       09270.522        11174.23       0
Bank Sta=6109.898,14246.44
Exp/Cntr=0.3,0.1

Type RM Length L Ch R = 1 ,15024.05,727.951500,727.951500,727.951500
XS GIS Cut Line= 6
871864.821570366772463.226403444871124.005247837771131.775494512
870663.448632223770113.323369469870404.812261724769362.222067614
870152.928775356768361.334244779869638.740190356766908.022156649
#Sta/Elev= 30
6174.604186.14386451.622143.98516729.008119.81036763.507108.87797266.487106.5365
7300.45294.515327515.21391.17059 7564.9197.544087627.58488.161527862.384 94.1237
7907.012 84.9859 8017.8385.278218139.45864.131658325.59956.048378500.83660.80188
8964.94946.919089514.44946.142869577.15925.404329639.63845.899589917.95545.95397
9979.42122.7308710010.1419.8419410051.0731.8528510225.3348.0508610587.99 38.7395
10839.5948.3162111453.1945.4157211751.22 53.315111943.2584.6361212185.66172.0957
#Mann= 3 , 0 , 0
6174.604  0.0451       06174.604  0.0451       012185.66  0.0451       0
#XS Ineff= 2 , 0
       09805.269        10951.53       0
Bank Sta=6174.604,12185.66
Exp/Cntr=0.3,0.1

Type RM Length L Ch R = 1 , 14296.1,970.602000,970.602000,970.602000
XS GIS Cut Line= 6
872395.308497233771025.923391535871323.246367118769225.607020108
870875.472058055768574.286114398 870696.14118926768279.539260177
870311.954581405767527.781551202870030.499661106766903.239175337
#Sta/Elev= 30
7300.973248.67977372.022224.70597383.684213.26387407.007205.31957453.655197.1637
7558.612194.57687628.584 168.366 7663.57139.20847733.486136.99227814.767111.3207
7884.437100.12757926.03182.902618128.27979.520018348.89965.067738372.12257.25119
8708.85744.924689065.59344.554049350.14334.416349385.32840.859749919.59942.83115
9968.65619.564419987.91818.1743910051.0527.8833910174.1530.3321410225.3143.95639
10467.9236.0160910765.4346.4806211655.0645.2826111786.3566.5170912061.74140.9516
#Mann= 3 , 0 , 0
7300.973  0.0409       07300.973  0.0409       012061.74  0.0409       0
#XS Ineff= 2 , 0
       09408.322           10869       0
Bank Sta=7300.973,12061.74
Exp/Cntr=0.3,0.1

Type RM Length L Ch R = 1 , 13325.5,831.488200,831.488200,831.488200
XS GIS Cut Line= 6
873382.747887519770376.869929768872609.754941957769231.556879662
 872299.49432981768799.083963425872059.502358326768486.151406144
871548.111489587 767897.76113929868849.511960358764598.412551151
#Sta/Elev= 30
7160.706214.58617192.758189.80367228.878 186.3477264.998162.91997355.297126.3962
7463.656  99.1337511.21372.512377535.23166.221127734.28464.477247848.05155.07017
7956.57757.092147980.69347.735558599.49139.018839602.75837.247319691.07928.58965
9726.86438.625849823.65641.662099863.99729.936779985.02217.1842610038.9819.22387
10106.4742.75808 12087.242.3147212638.4645.5391812764.8451.6450912849.3347.85741
13391.8662.0675314153.9965.3295514399.4272.2701914476.92 98.310714511.2698.26661
#Mann= 3 , 0 , 0
7160.706  0.0488       07160.706  0.0488       014511.26  0.0488       0
#XS Ineff= 2 , 0
       09050.836        11094.95       0
Bank Sta=7160.706,14511.26
Exp/Cntr=0.3,0.1

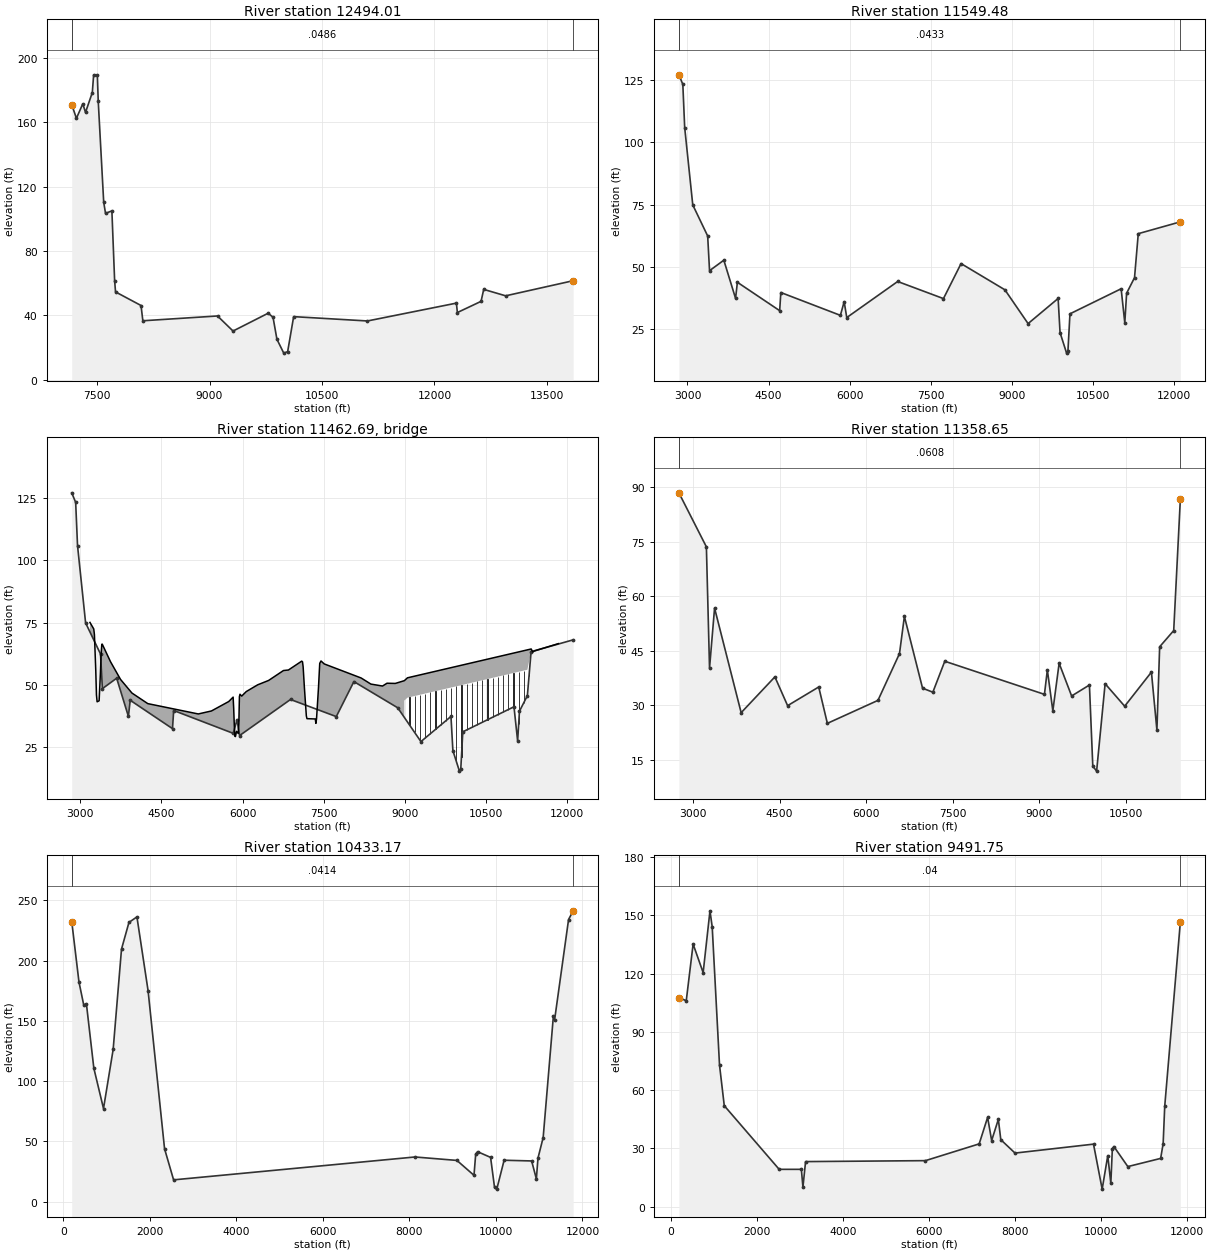
Type RM Length L Ch R = 1 ,12494.01,944.526700,944.526700,944.526700
XS GIS Cut Line= 4
874090.257741816769906.613653663873862.362222713769574.159466265
873079.986499134768440.200109889869938.573564593764667.683435628
#Sta/Elev= 30
7161.275171.06727223.633162.52687308.719 171.5417345.091166.20987435.871178.5797
7453.557189.58377502.702189.39067514.826173.14667587.618110.38427611.917 103.405
7696.961104.91797733.40961.557497745.55854.516498085.73646.054668110.03436.55596
9106.07839.541719313.14530.171859781.61641.250929846.682  38.7619898.73425.06193
9989.82616.4256910041.8817.3548810121.8639.1278211106.3936.4358512293.14 47.5412
12306.1641.6778412622.2448.6398212657.5156.0833112950.4252.0843713851.2261.48436
#Mann= 3 , 0 , 0
7161.275  0.0486       07161.275  0.0486       013851.22  0.0486       0
#XS Ineff= 2 , 0
       09062.027        11432.37       0
Bank Sta=7161.275,13851.22
Exp/Cntr=0.3,0.1

Type RM Length L Ch R = 1 ,11549.48,190.838400,190.838400,190.838400
XS GIS Cut Line= 6
876493.039839044773408.205997219875632.206374067771805.976702149
874896.285743266769859.681197899874026.634274368768396.786733559
872650.380341133766312.069734156872070.658201953765296.367806276
#Sta/Elev= 30
2841.228127.24972913.822123.40972948.278105.97913097.58774.871433373.23462.35013
3407.68948.388283671.851 52.60013888.86837.231473922.46843.718414704.37432.28221
4725.75639.597725826.92630.395995896.74635.897285944.52729.506596885.90444.02924
7732.28237.144918057.79751.239278868.157 40.68539296.94827.075389852.35937.19634
9887.78223.4616610008.6715.1855410033.8716.0952310071.0131.0083511017.35 41.0999
11084.8527.35832 11118.6 39.316911264.8545.5700911333.8663.2872812111.8468.04723
#Mann= 3 , 0 , 0
2841.228  0.0433       02841.228  0.0433       012111.84  0.0433       0
#XS Ineff= 2 , 0
       09045.263        11152.51       0
Bank Sta=2841.228,12111.84
Exp/Cntr=0.3,0.1

Type RM Length L Ch R = 3 ,11462.69,,,
BEGIN DESCRIPTION:
END DESCRIPTION:
Bridge Culvert--1,0,-1,-1, 0
Deck Dist Width WeirC Skew NumUp NumDn MinLoCord MaxHiCord MaxSubmerge Is_Ogee
34.419200,122.000000,2.6,0, 60, 60, , , 0.95, 0, 0,0,,
 3177.96 3248.43 3260.81 3285.58 3297.96 3310.34 3347.49 3371.50 3384.64 3397.02
 3405.41 3558.02 3743.73 3954.23 4247.11 5180.64 5423.63 5743.62 5825.08 5835.65
 5846.21 5856.77 5867.34 5888.47 5920.16 5930.73 5941.29 5951.85 5983.55 6068.06
 6279.36 6480.68 6755.14 6847.50 7093.12 7107.84 7119.63 7143.20 7178.56 7190.34
 7343.56 7355.35 7367.13 7402.49 7426.07 7449.64 7508.79 8191.73 8371.56 8586.70
 8669.49 8823.26 8990.06 8990.06 9047.9911335.1511365.4711390.0611390.0611838.32
   75.07   72.43   70.12   55.64   45.89   43.10   43.50   54.68   62.33   66.26
   66.32   59.25   52.10   46.63   42.37   38.21   39.41   43.21   44.99   40.36
   33.92   29.26   29.09   31.21   30.34   34.49   45.21   46.14   45.40   47.23
   49.95   51.70   55.69   55.91   59.48   59.21   57.15   48.65   37.40   36.31
   36.19   34.42   36.28   48.62   58.58   59.54   58.36   52.69   50.24   49.45
   50.58   50.50   51.61   51.61   52.76   64.37   63.13   63.53   63.53   66.53
 -924.93 -927.57 -929.88 -944.36 -954.11 -956.90 -956.50 -945.32 -937.67 -933.74
 -933.68 -940.75 -947.90 -953.37 -957.63 -961.79 -960.59 -956.79 -955.01 -959.64
 -966.08 -970.74 -970.91 -968.79 -969.66 -965.51 -954.79 -953.86 -954.60 -952.77
 -950.05 -948.30 -944.31 -944.09 -940.52 -940.79 -942.85 -951.35 -962.60 -963.69
 -963.81 -965.58 -963.72 -951.38 -941.42 -940.46 -941.64 -947.31 -949.76 -950.55
 -949.42 -949.50 -948.39   43.61   44.76   56.37   55.13   55.53 -936.47 -933.47
 3177.96 3248.43 3260.81 3285.58 3297.96 3310.34 3347.49 3371.50 3384.64 3397.02
 3405.41 3558.02 3743.73 3954.23 4247.11 5180.64 5423.63 5743.62 5825.08 5835.65
 5846.21 5856.77 5867.34 5888.47 5920.16 5930.73 5941.29 5951.85 5983.55 6068.06
 6279.36 6480.68 6755.14 6847.50 7093.12 7107.84 7119.63 7143.20 7178.56 7190.34
 7343.56 7355.35 7367.13 7402.49 7426.07 7449.64 7508.79 8191.73 8371.56 8586.70
 8669.49 8823.26 9003.39 9003.39 9047.9911335.1511365.4711403.3911403.3911838.32
   75.07   72.43   70.12   55.64   45.89   43.10   43.50   54.68   62.33   66.26
   66.32   59.25   52.10   46.63   42.37   38.21   39.41   43.21   44.99   40.36
   33.92   29.26   29.09   31.21   30.34   34.49   45.21   46.14   45.40   47.23
   49.95   51.70   55.69   55.91   59.48   59.21   57.15   48.65   37.40   36.31
   36.19   34.42   36.28   48.62   58.58   59.54   58.36   52.69   50.24   49.45
   50.58   50.50   51.63   51.63   52.76   64.37   63.13   63.58   63.58   66.53
 -924.93 -927.57 -929.88 -944.36 -954.11 -956.90 -956.50 -945.32 -937.67 -933.74
 -933.68 -940.75 -947.90 -953.37 -957.63 -961.79 -960.59 -956.79 -955.01 -959.64
 -966.08 -970.74 -970.91 -968.79 -969.66 -965.51 -954.79 -953.86 -954.60 -952.77
 -950.05 -948.30 -944.31 -944.09 -940.52 -940.79 -942.85 -951.35 -962.60 -963.69
 -963.81 -965.58 -963.72 -951.38 -941.42 -940.46 -941.64 -947.31 -949.76 -950.55
 -949.42 -949.50 -948.37   43.63   44.76   56.37   55.13   55.58 -936.42 -933.47
Pier Skew, UpSta & Num, DnSta & Num=  ,9084.22, 2 ,9097.55, 2 , 0 , 0 , 0 ,,
    4.00    4.00
 -947.26   52.74
    4.00    4.00
 -947.19   52.81
Pier Skew, UpSta & Num, DnSta & Num=  ,9180.38, 2 ,9193.71, 2 , 0 , 0 , 0 ,,
    4.00    4.00
 -946.76   53.24
    4.00    4.00
 -946.69   53.31
Pier Skew, UpSta & Num, DnSta & Num=  ,9276.54, 2 ,9289.87, 2 , 0 , 0 , 0 ,,
    4.00    4.00
 -946.26   53.74
    4.00    4.00
 -946.20   53.80
Pier Skew, UpSta & Num, DnSta & Num=  ,9372.70, 2 ,9386.03, 2 , 0 , 0 , 0 ,,
    4.00    4.00
 -945.77   54.23
    4.00    4.00
 -945.70   54.30
Pier Skew, UpSta & Num, DnSta & Num=  ,9468.86, 2 ,9482.19, 2 , 0 , 0 , 0 ,,
    4.00    4.00
 -945.27   54.73
    4.00    4.00
 -945.20   54.80
Pier Skew, UpSta & Num, DnSta & Num=  ,9565.02, 2 ,9578.35, 2 , 0 , 0 , 0 ,,
    4.00    4.00
 -944.77   55.23
    4.00    4.00
 -944.71   55.29
Pier Skew, UpSta & Num, DnSta & Num=  ,9661.18, 2 ,9674.51, 2 , 0 , 0 , 0 ,,
    4.00    4.00
 -944.28   55.72
    4.00    4.00
 -944.21   55.79
Pier Skew, UpSta & Num, DnSta & Num=  ,9757.34, 2 ,9770.67, 2 , 0 , 0 , 0 ,,
    4.00    4.00
 -943.78   56.22
    4.00    4.00
 -943.71   56.29
Pier Skew, UpSta & Num, DnSta & Num=  ,9853.50, 2 ,9866.83, 2 , 0 , 0 , 0 ,,
    4.00    4.00
 -943.28   56.72
    4.00    4.00
 -943.22   56.78
Pier Skew, UpSta & Num, DnSta & Num=  ,9949.66, 2 ,9962.99, 2 , 0 , 0 , 0 ,,
    4.00    4.00
 -942.79   57.21
    4.00    4.00
 -942.72   57.28
Pier Skew, UpSta & Num, DnSta & Num=  ,10045.82, 2 ,10059.15, 2 , 0 , 0 , 0 ,,
    4.00    4.00
 -942.29   57.71
    4.00    4.00
 -942.22   57.78
Pier Skew, UpSta & Num, DnSta & Num=  ,10141.98, 2 ,10155.31, 2 , 0 , 0 , 0 ,,
    4.00    4.00
 -941.79   58.21
    4.00    4.00
 -941.73   58.27
Pier Skew, UpSta & Num, DnSta & Num=  ,10238.14, 2 ,10251.47, 2 , 0 , 0 , 0 ,,
    4.00    4.00
 -941.30   58.70
    4.00    4.00
 -941.23   58.77
Pier Skew, UpSta & Num, DnSta & Num=  ,10334.30, 2 ,10347.63, 2 , 0 , 0 , 0 ,,
    4.00    4.00
 -940.80   59.20
    4.00    4.00
 -940.73   59.27
Pier Skew, UpSta & Num, DnSta & Num=  ,10430.46, 2 ,10443.79, 2 , 0 , 0 , 0 ,,
    4.00    4.00
 -940.30   59.70
    4.00    4.00
 -940.24   59.76
Pier Skew, UpSta & Num, DnSta & Num=  ,10526.62, 2 ,10539.95, 2 , 0 , 0 , 0 ,,
    4.00    4.00
 -939.81   60.19
    4.00    4.00
 -939.74   60.26
Pier Skew, UpSta & Num, DnSta & Num=  ,10622.78, 2 ,10636.11, 2 , 0 , 0 , 0 ,,
    4.00    4.00
 -939.31   60.69
    4.00    4.00
 -939.24   60.76
Pier Skew, UpSta & Num, DnSta & Num=  ,10718.94, 2 ,10732.27, 2 , 0 , 0 , 0 ,,
    4.00    4.00
 -938.82   61.18
    4.00    4.00
 -938.75   61.25
Pier Skew, UpSta & Num, DnSta & Num=  ,10815.10, 2 ,10828.43, 2 , 0 , 0 , 0 ,,
    4.00    4.00
 -938.32   61.68
    4.00    4.00
 -938.25   61.75
Pier Skew, UpSta & Num, DnSta & Num=  ,10911.26, 2 ,10924.59, 2 , 0 , 0 , 0 ,,
    4.00    4.00
 -937.82   62.18
    4.00    4.00
 -937.75   62.25
Pier Skew, UpSta & Num, DnSta & Num=  ,11007.42, 2 ,11020.75, 2 , 0 , 0 , 0 ,,
    4.00    4.00
 -937.33   62.67
    4.00    4.00
 -937.26   62.74
Pier Skew, UpSta & Num, DnSta & Num=  ,11103.58, 2 ,11116.91, 2 , 0 , 0 , 0 ,,
    4.00    4.00
 -936.83   63.17
    4.00    4.00
 -936.76   63.24
Pier Skew, UpSta & Num, DnSta & Num=  ,11199.74, 2 ,11213.07, 2 , 0 , 0 , 0 ,,
    4.00    4.00
 -936.33   63.67
    4.00    4.00
 -936.26   63.74
Pier Skew, UpSta & Num, DnSta & Num=  ,11295.90, 2 ,11309.23, 2 , 0 , 0 , 0 ,,
    4.00    4.00
 -935.84   64.16
    4.00    4.00
 -935.77   64.23
BR Coef=-1 , 0 , 0 ,, 0 ,,,0.8,0,1,0,
WSPro=,,,, 1 ,,,, 0 ,,,, 0 ,,,,-1 ,-1 ,-1 , 0 , 0 , 0 , 0 , 0
BC Design=,, 0 ,, 0 ,,,,,,

Type RM Length L Ch R = 1 ,11358.65,925.471400,925.471400,925.471400
XS GIS Cut Line= 6
876757.270882984773351.714005226875922.047444329771503.525760174
875366.024841699 770033.53332178874980.352896746769408.878753522
873560.961661143767346.794036944872573.434432101765783.036626694
#Sta/Elev= 30
2754.83888.494123231.02873.611483285.54840.205793372.77956.735263833.347 27.9217
4417.68237.790014638.18529.857455177.14635.000745326.82624.981576203.52531.31568
6576.34744.192396661.28354.44591 6975.9334.669277154.37433.568647360.97142.09347
9087.64932.972079137.96639.69589 9233.0428.430269342.084 41.53189558.419 32.5279
9866.89135.544489925.34913.200889991.47911.8225810138.6935.90346 10477.529.70818
10940.91 39.102111035.9723.12458 11083.546.0785311327.0750.5465711441.9486.70327
#Mann= 3 , 0 , 0
2754.838  0.0608       02754.838  0.0608       011441.94  0.0608       0
#XS Ineff= 2 , 0
       09063.137        11096.89       0
Bank Sta=2754.838,11441.94
Exp/Cntr=0.3,0.1

Type RM Length L Ch R = 1 ,10433.17,941.424600,941.424600,941.424600
XS GIS Cut Line= 6
879842.513038709774480.626347996874752.360118131767326.900855207
874354.304426532  766786.5474237873979.927443859766331.228534605
873696.936691815765954.397375662873095.121762175765055.556553735
#Sta/Elev= 30
192.6773232.3652359.4776182.2981470.1643 163.051531.6569164.1842703.7669110.6534
927.090377.215561150.414126.24131343.359209.46621515.538231.62081700.133236.1834
1958.001174.94392338.75443.850152547.55518.076918128.77537.054789098.36634.20319
9493.00321.842369532.92939.592949576.07641.436999876.69336.717699967.95511.85061
10020.0810.3927610189.2434.3522610825.7333.7640810935.4218.8450510971.6535.99223
11092.4153.1802311329.23154.211611357.14150.915111679.69 234.01811786.31241.2208
#Mann= 3 , 0 , 0
192.6773  0.0414       0192.6773  0.0414       011786.31  0.0414       0
#XS Ineff= 2 , 0
       09070.032        11003.29       0
Bank Sta=192.6773,11786.31
Exp/Cntr=0.3,0.1

Type RM Length L Ch R = 1 , 9491.75,827.980200,827.980200,827.980200
XS GIS Cut Line= 6
880523.426140833773964.288681719878097.396089478770552.115325604
875386.059287561766719.666886237875010.165405808766166.781581707
874627.843065204 765564.29315641873860.930535889764405.444358419
#Sta/Elev= 30
188.2929107.6944 359.199106.0619518.7081135.2513751.8366120.5596  910.39152.3963
962.1624144.18541132.204 72.90281242.63451.988292518.70619.199863034.04319.19792
3070.85210.050993132.20223.188365917.74923.680717166.54432.319377362.68945.98418
7456.35334.031387612.04544.954037669.01934.477927999.45827.57898 9823.2632.18657
10024.759.00377110154.96 26.269110225.9812.03715 10261.529.8869710297.0130.95419
10621.0820.6198111383.5124.8262111441.9432.4366911478.4251.6595411841.41146.5654
#Mann= 3 , 0 , 0
188.2929    0.04       0188.2929    0.04       011841.41    0.04       0
#XS Ineff= 2 , 0
       08934.625        10442.37       0
Bank Sta=188.2929,11841.41
Exp/Cntr=0.3,0.1