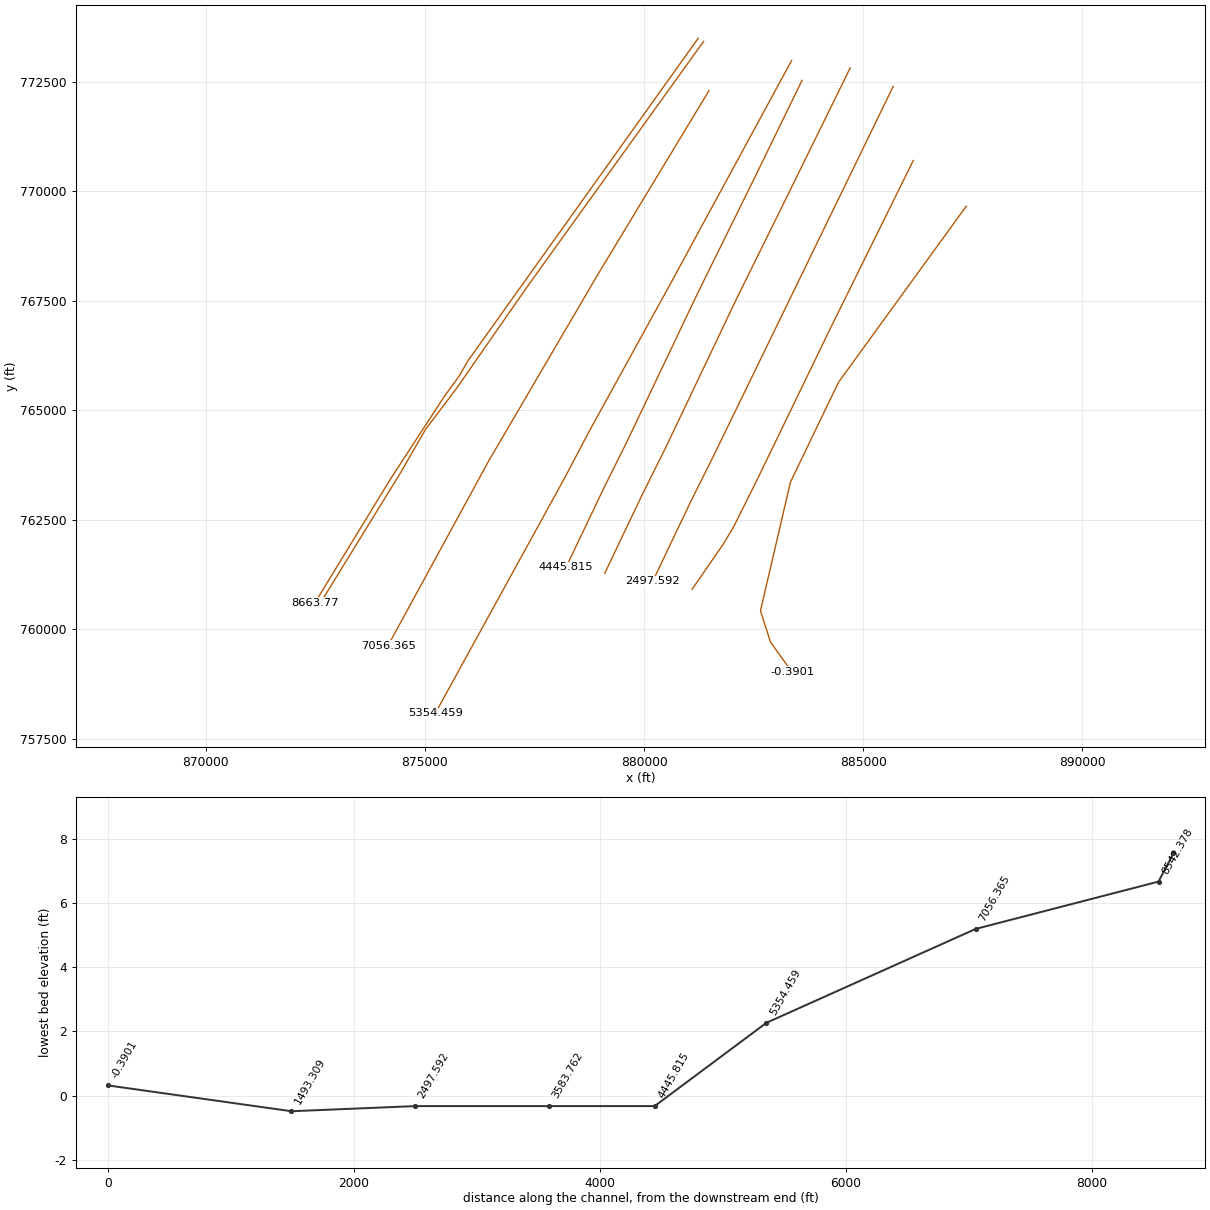
HEC-RAS study 9741_ras.prj: 9741

--- 9741_ras.g01 (geometry) --- (continued)

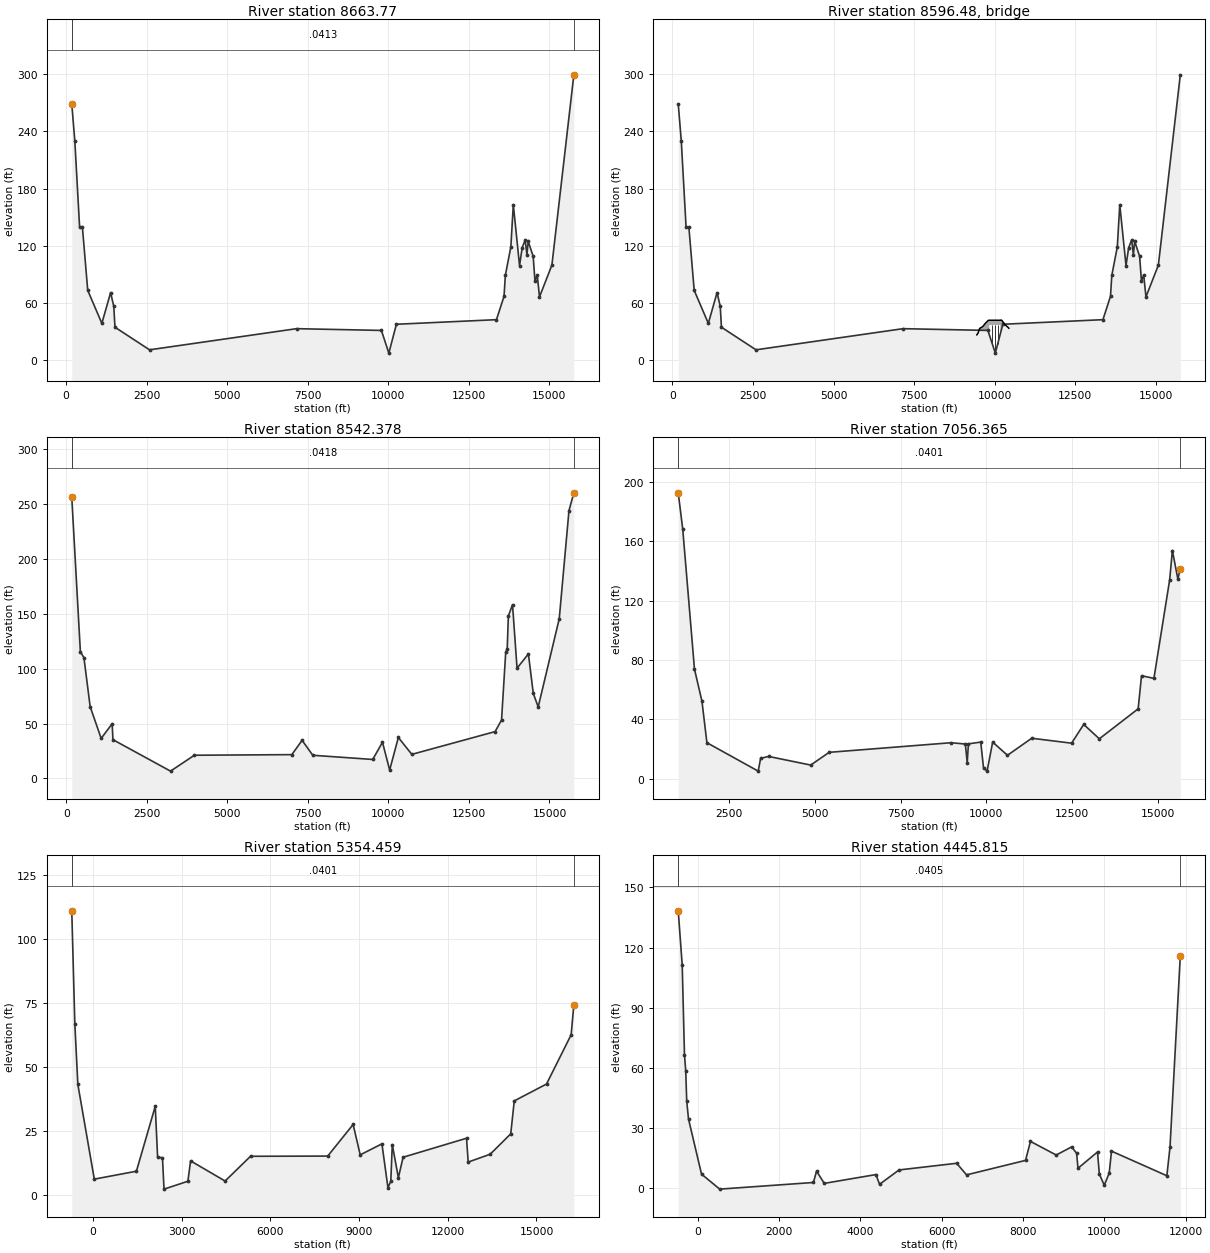
Type RM Length L Ch R = 1 , 8663.77,121.391900,121.391900,121.391900
XS GIS Cut Line= 6
881234.776489063773492.091015903875978.137173831 766128.82637135
875781.932292124765785.312124911875444.046678018765323.912906236
 874213.08431377763434.454116976872488.501243783760609.262710028
#Sta/Elev= 30
179.1568 268.757274.2267229.7534422.2126139.5872508.5377139.8195674.330773.33286
1112.81438.744861384.12170.952721482.77856.573171519.77534.708412591.968 11.0207
7155.78233.187389788.00931.33757 10018.27.55141910252.7537.8052813357.9542.60868
13592.9967.0884313633.2588.9824113804.52118.918913880.73163.128714074.3199.30496
14156.27118.023914249.93 126.21714303.15110.491614343.55124.720414497.22108.9149
14553.4682.9939114623.4389.48239 14693.4 66.491515078.2299.7533315759.34299.2175
#Mann= 3 , 0 , 0
179.1568  0.0413       0179.1568  0.0413       015759.34  0.0413       0
#XS Ineff= 2 , 0
       08833.521        10210.87       0
Bank Sta=179.1568,15759.34
Exp/Cntr=0.3,0.1

Type RM Length L Ch R = 3 , 8596.48,,,
BEGIN DESCRIPTION:
END DESCRIPTION:
Bridge Culvert--1,0,-1,-1, 0
Deck Dist Width WeirC Skew NumUp NumDn MinLoCord MaxHiCord MaxSubmerge Is_Ogee
43.695950,34.000000,2.6,0, 37, 36, , , 0.95, 0, 0,0,,
 9445.35 9451.43 9459.73 9471.25 9482.76 9494.27 9505.78 9511.98 9528.81 9532.16
 9540.32 9563.35 9597.89 9620.91 9633.07 9653.25 9679.40 9691.49 9703.57 9743.05
 9796.45 9807.83 9830.89 9830.8910175.8910175.8910201.2410202.9710215.5710241.87
10275.7710327.2510360.5210364.4010389.1710426.3310438.63
   26.70   26.83   27.31   28.26   28.48   29.43   31.30   31.63   33.02   33.47
   33.57   34.12   34.71   35.27   35.62   36.35   37.60   37.99   38.63   40.00
   41.73   41.99   42.00   42.00   42.02   42.02   42.02   42.21   42.01   40.92
   39.37   37.28   36.13   35.93   35.29   34.12   33.62
 -973.30 -973.17 -972.69 -971.74 -971.52 -970.57 -968.70 -968.37 -966.98 -966.53
 -966.43 -965.88 -965.29 -964.73 -964.38 -963.65 -962.40 -962.01 -961.37 -960.00
 -958.27 -958.01 -958.00   37.00   37.02 -957.98 -957.98 -957.79 -957.99 -959.08
 -960.63 -962.72 -963.87 -964.07 -964.71 -965.88 -966.38
 9445.35 9451.43 9459.73 9471.25 9482.76 9494.27 9505.78 9511.98 9528.81 9532.16
 9540.32 9563.35 9597.89 9633.07 9655.45 9679.40 9691.49 9703.57 9743.05 9800.28
 9807.83 9832.21 9832.2110177.2110177.2110201.2410202.9710215.5710241.8710275.77
10327.2510360.5210364.4010389.1710426.3310438.63
   26.70   26.83   27.31   28.26   28.48   29.43   31.30   31.63   33.02   33.47
   33.57   34.12   34.71   35.62   36.44   37.60   37.99   38.63   40.00   41.84
   41.99   42.00   42.00   42.02   42.02   42.02   42.21   42.01   40.92   39.37
   37.28   36.13   35.93   35.29   34.12   33.62
 -973.30 -973.17 -972.69 -971.74 -971.52 -970.57 -968.70 -968.37 -966.98 -966.53
 -966.43 -965.88 -965.29 -964.38 -963.56 -962.40 -962.01 -961.37 -960.00 -958.16
 -958.01 -958.00   37.00   37.02 -957.98 -957.98 -957.79 -957.99 -959.08 -960.63
 -962.72 -963.87 -964.07 -964.71 -965.88 -966.38
Pier Skew, UpSta & Num, DnSta & Num=  ,9916.14, 2 ,9917.46, 2 , 0 , 0 , 0 ,,
    4.00    4.00
 -958.00   42.00
    4.00    4.00
 -958.00   42.00
Pier Skew, UpSta & Num, DnSta & Num=  ,10003.39, 2 ,10004.71, 2 , 0 , 0 , 0 ,,
    4.00    4.00
 -957.99   42.01
    4.00    4.00
 -957.99   42.01
Pier Skew, UpSta & Num, DnSta & Num=  ,10090.64, 2 ,10091.96, 2 , 0 , 0 , 0 ,,
    4.00    4.00
 -957.99   42.01
    4.00    4.00
 -957.99   42.01
BR Coef=-1 , 0 , 0 ,, 0 ,,,0.8,0,1,0,
WSPro=,,,, 1 ,,,, 0 ,,,, 0 ,,,,-1 ,-1 ,-1 , 0 , 0 , 0 , 0 , 0
BC Design=,, 0 ,, 0 ,,,,,,

Type RM Length L Ch R = 1 ,8542.378,1486.012800,1486.012800,1486.012800
XS GIS Cut Line= 6
881359.086271361773421.508720032877333.552045431767822.562269649
875709.214733701765487.191602123875009.932907292764561.610430271
874433.799061597 763563.71988457872582.709010591760555.423373605
#Sta/Elev= 30
 170.742255.8595437.8105115.3828548.8276 109.823741.360365.38584 1082.9636.46582
1424.55949.76647  1449.3 35.28733236.5286.6721373976.43921.128647002.21221.68242
7320.942 34.71077651.74921.103059513.04917.292469816.11432.9561510038.327.653821
10308.6137.2882510726.3621.9349713311.39 42.634713511.7153.11529 13641.1114.6608
13688.06118.028313723.28147.806413852.42158.1787 13993.3 100.37214345.43113.3003
14497.4877.3716214649.5265.0741915302.91145.307415605.46243.791215756.25259.9284
#Mann= 3 , 0 , 0
 170.742  0.0418       0 170.742  0.0418       015756.25  0.0418       0
#XS Ineff= 2 , 0
       08819.335        10207.32       0
Bank Sta=170.742,15756.25
Exp/Cntr=0.3,0.1

Type RM Length L Ch R = 1 ,7056.365,1701.906100,1701.906100,1701.906100
XS GIS Cut Line= 5
881482.942097846 772300.02826433878943.080972879768098.418828878
877072.777074039764902.927777218876457.043466656763851.367667196
874156.729215985759632.186344858
#Sta/Elev= 30
1018.141192.49491149.475168.05621491.42173.857771710.05352.203041853.65924.32195
3349.3535.1973273419.463 13.78183653.16515.082094880.1019.2746865417.61617.84682
8972.66624.313479388.39823.439029442.56810.829549477.32823.558329836.54624.73776
9917.6637.38976210021.965.23248110184.1924.7463110615.4915.8569111323.1627.33025
 12484.923.9963812837.9836.6321513293.5726.94568 14425.547.1346714523.6669.40724
 14885.167.6249315344.69134.008415423.44153.6396 15582.9134.503715654.44141.5598
#Mann= 3 , 0 , 0
1018.141  0.0401       01018.141  0.0401       015654.44  0.0401       0
#XS Ineff= 2 , 0
       0 8647.48        10195.36       0
Bank Sta=1018.141,15654.44
Exp/Cntr=0.3,0.1

Type RM Length L Ch R = 1 ,5354.459,908.644000,908.644000,908.644000
XS GIS Cut Line= 5
883368.375551253772985.805828725880564.710414336767821.156907489
  878732.0794095764492.858186761878201.221679338763483.404028583
875234.570922666758085.040186937
#Sta/Elev= 30
-713.181111.1666-609.85866.90877-507.45243.2378348.46652 6.180011472.4019.274495
2109.59434.673082189.24414.773642354.10314.539182405.4342.2686993213.4775.346159
3304.33313.325444471.0975.4345915330.24315.119427940.93915.202428800.61827.57541
9039.55215.675579773.95319.987039977.3262.85216710073.815.36645710124.4119.69321
 10329.86.73266810489.5514.7447112634.7322.1834512691.0112.8576813433.4615.91726
14129.5123.9034214248.2736.7920615339.0243.3893716171.9962.6605616263.2374.37385
#Mann= 3 , 0 , 0
-713.181  0.0401       0-713.181  0.0401       016263.23  0.0401       0
#XS Ineff= 2 , 0
       08352.302        10133.16       0
Bank Sta=-713.181,16263.23
Exp/Cntr=0.3,0.1

Type RM Length L Ch R = 1 ,4445.815,862.053400,862.053400,862.053400
XS GIS Cut Line= 6
883605.978647107772532.993613319882477.267787313770215.316221594
 881227.19500546767682.573134958879609.560054573764285.611547638
879088.379633917763240.434266739878218.343378682761416.412150724
#Sta/Elev= 30
-484.523138.2872 -386.65111.2523-331.03666.64978-299.57358.33485-275.42243.34227
-231.05534.5358288.697067.136221536.5437-0.328082840.9032.9813222918.9658.631733
3108.5442.5362934379.8396.9251314469.0532.0784014948.3679.2247286366.08912.54728
 6609.766.776521 8060.7113.987218182.54523.438658815.06116.657689194.98820.69933
9317.90517.547449351.42810.054949831.92418.18046 9876.38 7.214829998.2521.594899
10120.137.71456510175.5218.5967211538.286.33536911615.84 20.7262 11869.1115.9992
#Mann= 3 , 0 , 0
-484.523  0.0405       0-484.523  0.0405       0 11869.1  0.0405       0
#XS Ineff= 2 , 0
       08243.602        10184.09       0
Bank Sta=-484.523,11869.1
Exp/Cntr=0.3,0.1

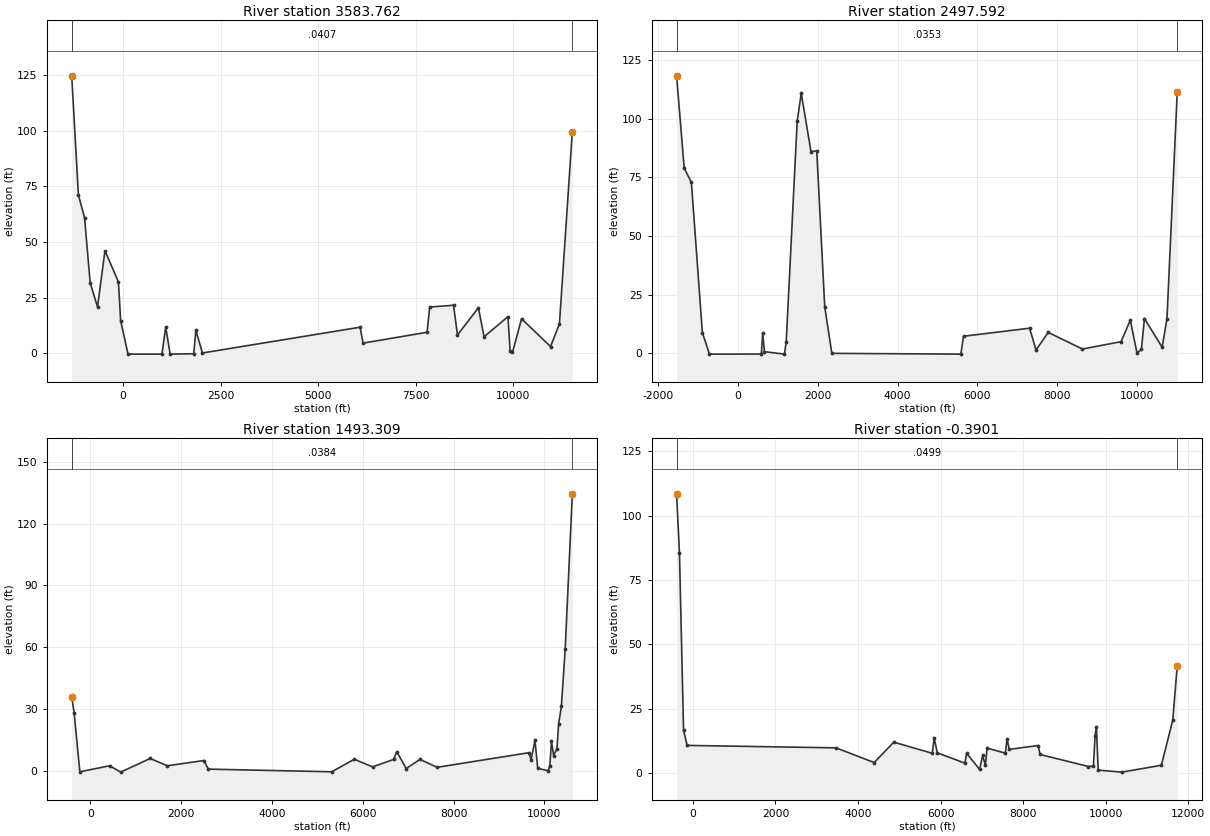
Type RM Length L Ch R = 1 ,3583.762,1086.169400,1086.169400,1086.169400
XS GIS Cut Line= 6
 884706.48439926772819.884957389883293.217461768769942.307058306
882113.903872343767552.847048926880496.312894274764155.855898382
879975.145954136763110.669194277879105.133307413761286.631184028
#Sta/Elev= 30
-1313.03 124.566-1140.4871.02731-984.50460.96309-839.671 31.6802-651.82220.83594
-460.87946.06739-115.50932.08172-59.804414.70199129.5919-0.32808998.5866-0.32808
1094.86911.833791208.291-0.328081811.877-0.149051867.58110.308052034.8320.183546
6072.51311.748446150.044 4.610817789.2749.4909857855.72920.82192 8466.1921.60139
8566.7588.2730439103.12120.487269248.387 7.461429859.78216.489069915.1781.291964
 9976.020.474382 10208.315.5223310951.613.07743911178.2113.2766211508.79 99.5191
#Mann= 3 , 0 , 0
-1313.03  0.0407       0-1313.03  0.0407       011508.79  0.0407       0
#XS Ineff= 2 , 0
       08129.848        10216.89       0
Bank Sta=-1313.03,11508.79
Exp/Cntr=0.3,0.1

Type RM Length L Ch R = 1 ,2497.592,1004.283300,1004.283300,1004.283300
XS GIS Cut Line= 5
885687.426272456772396.951582917883253.046880592767389.307417313
881591.217094806763972.714222243881070.066610237762927.515511349
880200.082797674761103.457227238
#Sta/Elev= 30
-1542.78118.2017-1351.58 78.8773-1171.2772.81303-895.7048.787904  -717.8-0.32808
583.1249-0.29326616.48198.720114 660.9580.7124281161.714-0.320071207.4594.951178
1481.92898.852691583.836110.80581828.45585.900771973.00286.253572173.14419.80256
2351.079       05586.846-0.328085653.5677.2909717310.47410.714497472.9621.441673
7777.5228.9146718637.7031.8429199604.6064.9825349837.269 14.159510003.090.183751
10114.251.669558 10191.814.8434610634.972.61799310756.8414.8241611013.37111.1743
#Mann= 3 , 0 , 0
-1542.78  0.0353       0-1542.78  0.0353       011013.37  0.0353       0
#XS Ineff= 2 , 0
       07243.956         10195.1       0
Bank Sta=-1542.78,11013.37
Exp/Cntr=0.3,0.1

Type RM Length L Ch R = 1 ,1493.309,1493.699200,1493.699200,1493.699200
XS GIS Cut Line= 6
886144.267364284770703.645116255  884207.6994363766779.493715576
882569.361763488763394.309286376882044.944855166 762342.51931775
881811.870541725761953.819424667881097.029321724760916.633590589
#Sta/Elev= 30
-409.15936.10788-354.913 28.1317-230.042-0.32808425.68632.589884671.0176-0.48829
  1317.86.1319351696.9482.6006892499.8515.1321132600.2140.969464 5316.08-0.32465
5816.0115.7496796215.9572.0455246682.5595.6777826749.2179.4590836957.1711.248104
7260.258 5.678777637.9841.8447899659.736 8.927489708.2065.5230499793.02914.92376
9853.6181.36489410083.780.17046610120.122.68830810156.4514.4214410204.897.550001
10277.5510.9627710313.8922.8786510374.4431.3234110459.3459.4277610615.81134.4095
#Mann= 3 , 0 , 0
-409.159  0.0384       0-409.159  0.0384       010615.81  0.0384       0
#XS Ineff= 2 , 0
       06034.368        10188.43       0
Bank Sta=-409.159,10615.81
Exp/Cntr=0.3,0.1

Type RM Length L Ch R = 1 , -0.3901,0.000000,0.000000,0.000000
XS GIS Cut Line= 6
887354.440326217769661.428602776884437.057500543765639.450740506
883341.063396011 763361.83917355 882656.99353678760426.571154181
882885.663950416759713.078110312883377.205346783759029.457030807
#Sta/Elev= 30
 -396.15108.4503-326.24585.53564-227.13916.58815-140.421 10.70123466.1749.750928
4391.336 4.03805 4865.2411.967195797.5447.6336975845.396   13.495920.8417.804266
6588.9843.821209 6632.097.6130536944.6081.3711477020.0436.8321717084.7022.943088
7127.3469.6694227568.4147.688519 7610.4213.225877662.9289.1599148366.03510.66175
8407.3747.1917429580.8472.5020589702.1092.6758789742.52914.472819774.42917.94257
9818.3131.09180210391.120.31764611349.012.98319511625.25 20.571611732.7141.50829
#Mann= 3 , 0 , 0
 -396.15  0.0499       0 -396.15  0.0499       011732.71  0.0499       0
#XS Ineff= 2 , 0
       05131.997         10201.4       0
Bank Sta=-396.15,11732.71
Exp/Cntr=0.3,0.1